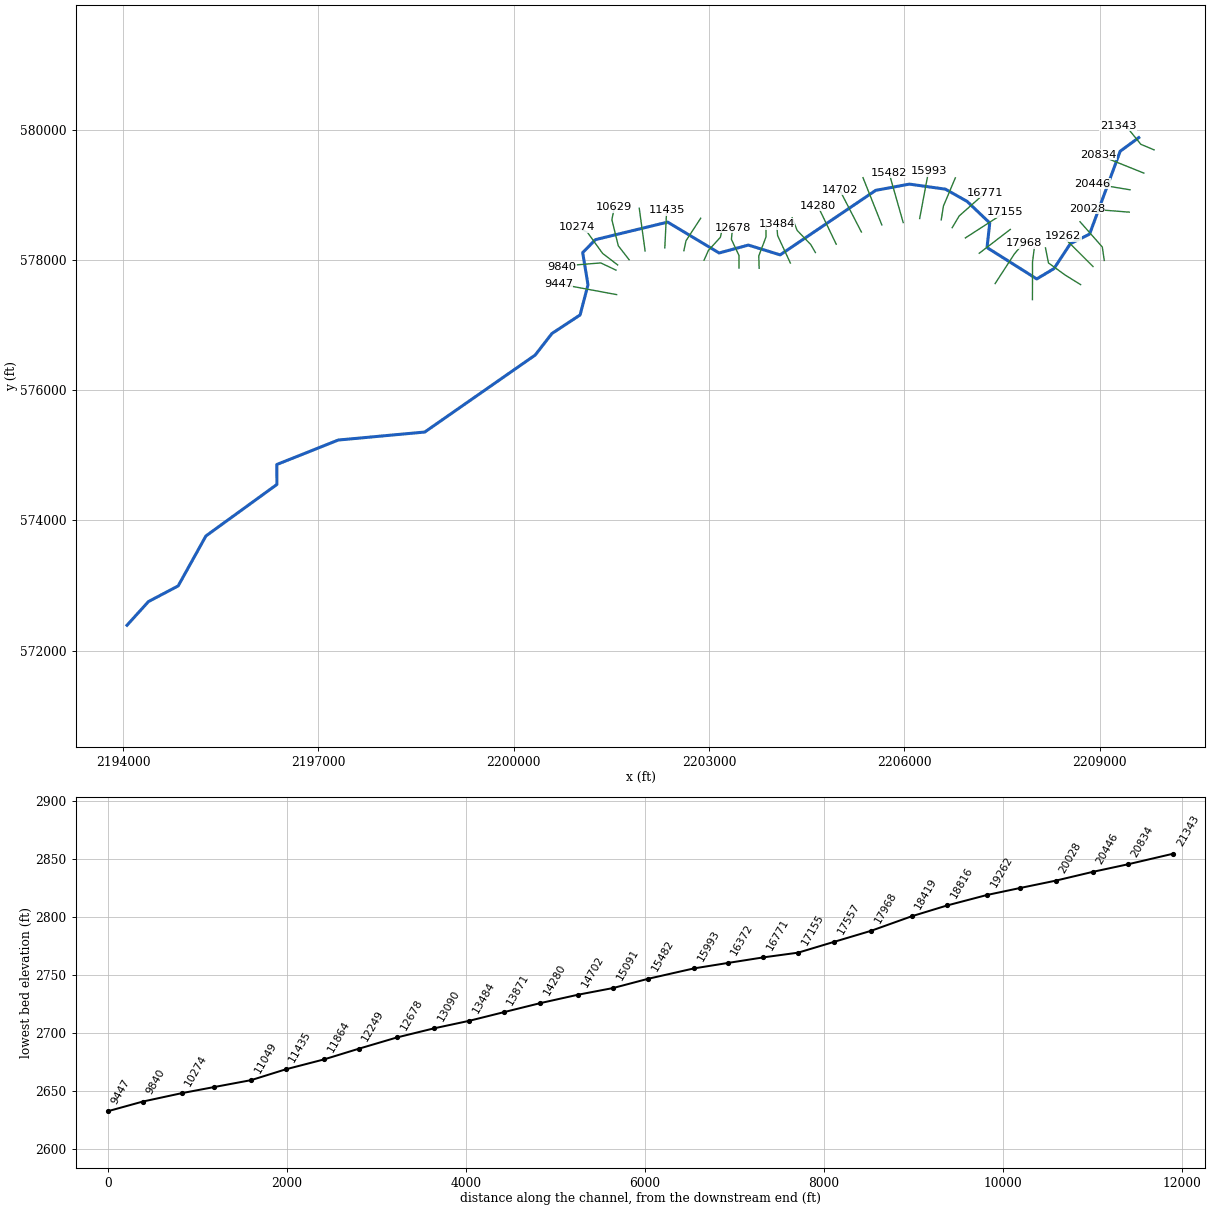
--- BFKELKRV.prj (project) ---

Proj Title=BFKELKRV
Current Plan=p01
Default Exp/Contr=0,0
English Units
Geom File=g01
Flow File=f01
Plan File=p01
BEGIN DESCRIPTION:
----------MODEL BY WOOD PLC 2022----------
AFH study
Randolph County, WV
HEC-RAS Version: RAS 6.2
Vertical Datum: NAVD88
Projection: NAD 1983 StatePlane West Virginia S FIPS 4702 (US Feet)
Terrain: 1-meter LIDAR (FEMA Region III 3DEP collected 2016-2018)
Land Use: 2019 NLCD
Hydrologic Method:
WV SIR2010-5033 regression equations
Additional Model Notes:
None
END DESCRIPTION:
DSS Export Rating Curves= 0
DSS Export Rating Curve Sorted= 0
DSS Export Volume Flow Curves= 0
DXF OffsetX= 0
DXF OffsetY= 0
DXF ScaleX= 0
DXF ScaleY= 0

--- BFKELKRV.p01 (plan) ---

Plan Title=Floodplain
Program Version=6.20
Short Identifier=Floodplain
Geom File=g01
Flow File=f01
Subcritical Flow
K Sum by GR= 0
Std Step Tol= 0.01
Critical Tol= 0.01
Num of Std Step Trials= 20
Max Error Tol= 0.3
Flow Tol Ratio= 0.001
Split Flow NTrial= 30
Split Flow Tol= 0.02
Split Flow Ratio= 0.02
Log Output Level= 0
Friction Slope Method= 1
Unsteady Friction Slope Method= 2
Unsteady Bridges Friction Slope Method= 1
Parabolic Critical Depth
Global Vel Dist= 0 , 0 , 0
Global Log Level= 0
CheckData=True
Encroach Param=-1 ,0,0, 0
Mapping Interval=1HOUR
Computation Time Step Use Courant=        0
Computation Time Step Use Time Series=    0
Computation Time Step Count To Double=0
Computation Time Step Max Doubling=0
Computation Time Step Max Halving=0
Computation Time Step Residence Courant=0
Run HTab= 0
Run UNet= 0
Run Sediment= 0
Run PostProcess= 0
Run WQNet= 0
Run RASMapper=-1
UNET Theta= 0
UNET Theta Warmup= 0
UNET ZTol= 0
UNET ZSATol= 0
UNET MxIter= 0
UNET Max Iter WO Improvement= 0
UNET MaxInSteps= 0
UNET DtIC= 0
UNET DtMin= 0
UNET MaxCRTS= 0
UNET WFStab= 0
UNET SFStab= 0
UNET WFX= 1
UNET SFX= 1
UNET Gravity=32.174
UNET 1D Methodology=Finite Difference
UNET DSS MLevel= 1
UNET Pardiso=0
UNET DZMax Abort= 0
UNET Use Existing IB Tables= 0
UNET Froude Reduction=False
UNET Froude Limit= 0
UNET Froude Power= 0
UNET D1 Cores= 0
UNET WindReference=Eulerian
UNET WindDragFormulation=Hsu (1988)
UNET D2 Coriolis=0
UNET D2 Cores= 0
UNET D2 Theta= 1
UNET D2 Theta Warmup= 1
UNET D2 Z Tol= 0.01
UNET D2 Volume Tol= 0.01
UNET D2 Max Iterations= 20
UNET D2 Equation= 0
UNET D2 RampUpFraction=0.1
UNET D2 TimeSlices= 1
UNET D2 Turbulence Formulation=Non-Conservative (original)
UNET D2 Eddy Viscosity=0.3
UNET D2 Transverse Eddy Viscosity=0.1
UNET D2 Smagorinsky Mixing=0
UNET D2 BCVolumeCheck=0
UNET D2 Cores=0
UNET D2 SolverType=PARDISO (Direct)
UNET D2 Minimum Iterations= 2147483647
UNET D2 Maximum Iterations= 2147483647
UNET D2 Restart Number= 10
UNET D2 Relaxation Coeff=1.3
UNET D2 SOR Precondition Iterations= 10
UNET D2 ILUT Maximum Fill= 8
UNET D2 ILUT Tolerance=1E-08
UNET D1D2 MaxIter= 0
UNET D1D2 ZTol=0.01
UNET D1D2 QTol=0.1
UNET D1D2 MinQTol=1
Write IC File= 0
Write IC File at Fixed DateTime=0
Write IC File at Sim End=0
Echo Input=False
Echo Parameters=False
Echo Output=False
Write Detailed= 0
HDF Write Warmup=0
HDF Write Time Slices=0
HDF Flush=0
HDF Compression= 1
HDF Chunk Size= 1
HDF Spatial Parts= 1
HDF Use Max Rows=0
HDF Fixed Rows= 1
Calibration Method= 0
Calibration Iterations= 20
Calibration Max Change=0.05
Calibration Tolerance=0.2
Calibration Maximum=1.5
Calibration Minimum=0.5
Calibration Optimization Method= 1
WQ AD Non Conservative
WQ ULTIMATE=-1
WQ Max Comp Step=1HOUR
WQ Output Interval=15MIN
WQ Output Selected Increments= 0
WQ Output face flow=0
WQ Output face velocity=0
WQ Output face area=0
WQ Output face dispersion=0
WQ Output cell volume=0
WQ Output cell surface area=0
WQ Output cell continuity=0
WQ Output cumulative cell continuity=0
WQ Output face conc=0
WQ Output face dconc_dx=0
WQ Output face courant=0
WQ Output face peclet=0
WQ Output face adv mass=0
WQ Output face disp mass=0
WQ Output cell mass=0
WQ Output cell source sink temp=0
WQ Output nsm pathways=0
WQ Output nsm derived pathways=0
WQ Create Restart=0
WQ Fixed Restart=0
WQ System Summary=0
WQ Write To DSS=0
Sorting and Armoring Iterations= 10
XS Update Threshold= 0.02
Bed Roughness Predictor= 0
Hydraulics Update Threshold= 0.02
Energy Slope Method= 1
Volume Change Method= 1
Sediment Retention Method= 0
Sediment TS Multiplier= 1
Warm Up Method= 0
XS Weighting Method= 0
Number of US Weighted Cross Sections= 1
Number of DS Weighted Cross Sections= 1
Upstream XS Weight=0
Main XS Weight=1
Downstream XS Weight=0
Number of DS XS's Weighted with US Boundary= 1
Upstream Boundary Weight= 1
Weight of XSs Associated with US Boundary= 0
Number of US XS's Weighted with DS Boundary= 1
Downstream Boundary Weight= 0.5
Weight of XSs Associated with DS Boundary= 0.5
Percentile Method= 0
Sediment Output Level= 3
Mass or Volume Output= 0
Output Increment Type= 1
Profile and TS Output Increment= 1
Transport Output Increment 1
XS Output Flag= 0
XS Output Increment= 10
Read HDF5 Sediment Hotstart= 0
Sediment Hotstart Type= 0
Write Gradation File= 0
Read Gradation Hotstart= 0
Write HDF5 File= 1
Write Binary Output= 1
Write DSS Sediment File= 0
DSS Sediment Output Type= 1
SV Curve= 0
Specific Gage Flag= 0
Subcell Erosion Methods= 0
Subcell Deposition Methods= 0
Advection Scheme= 1
Matrix Solver= 0
Implicit Weighting Factor= 1
Maximum Outer Loop Convergence Iterations= 5
Convergence Maximum Absolute= 0.001
Convergence RMSE= 0.0001
Grain Fractions Max Abs Error= 0.001
Max Subgrid Regions= 1
Max Subgrid Length Scale= 3.402823E+38
Initial Layer Thickness= 3.402823E+38
Min Layer Thickness= 3.402823E+38
Max Layer Thickness= 3.402823E+38
Number of Layers= 5

--- BFKELKRV.f01 (steady flow) ---

Flow Title=Flow
Program Version=6.20
Number of Profiles= 1
Profile Names=P100yr
River Rch & RM=BFKELKRV,Main,21343
    2210
River Rch & RM=BFKELKRV,Main,11864
    2460
River Rch & RM=BFKELKRV,Main,9012
    2940
Boundary for River Rch & Prof#=BFKELKRV,Main            , 1
Up Type= 0
Dn Type= 3
Dn Slope=0.015927
DSS Import GetInterval= 0
DSS Import GetPeak= 0
DSS Import FillOption= 0

--- BFKELKRV.g01 (geometry) ---

Geom Title=Geometry
Program Version=6.20

River Reach=BFKELKRV        ,Main
Reach XY= 30
     2209599.459      579877.746     2209313.996       579669.27
     2208844.127      578396.498     2208548.217      578248.475
  2208296.842543577866.3721326782208032.69330467577708.352238329
     2207269.001      578190.0562207310.92410406578567.547283092
     2206964.456      578897.8762206631.28476167579086.533304668
     2206076.664      579164.4362205559.86369533579068.652351352
     2204091.878      578077.7512203603.54050369578228.604980344
2203155.06730467578106.912371008     2202364.329      578580.821
     2201256.203      578312.027     2201059.496      578112.821
     2201140.743      577617.569     2201019.579      577155.073
     2200587.072      576870.443      2200329.91      576539.393
     2198634.085      575357.713     2197305.489      575234.658
     2196361.685      574859.0932196363.37305114574552.507031049
2195272.86115233573761.613980344     2194847.151      572994.933
      2194390.09      572753.897     2194061.377      572391.059

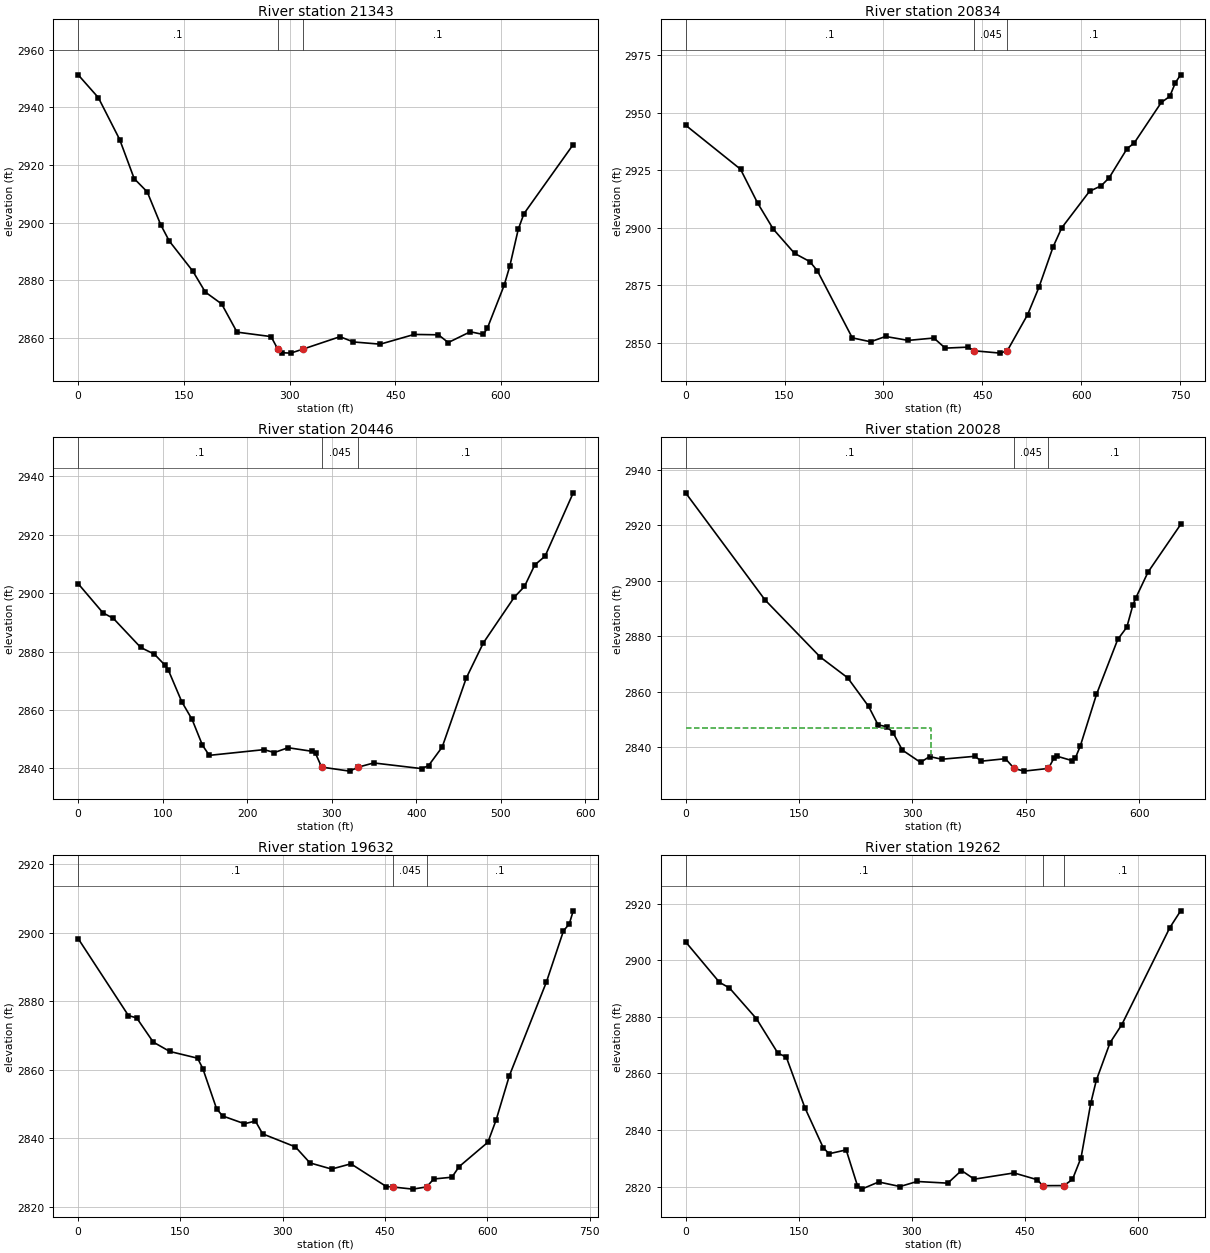
Type RM Length L Ch R = 1 ,21343   ,496.3,508.5,520
XS GIS Cut Line= 4
2209834.50056629579690.3947807042209631.40429951579775.637117832
2209405.28231693580054.6196838912209282.18275873580058.022378714
#Sta/Elev= 30
       0 2951.33    28.6 2943.42    58.9 2928.87    79.5 2915.29      98 2910.69
     117 2899.36   129.2 2893.66   162.8 2883.13   180.4 2875.91   203.6 2871.79
   225.4    2862   273.7 2860.45  283.192856.135   289.1 2854.85   301.6 2854.71
  319.382856.132   371.5 2860.41   390.6 2858.59   428.7 2857.82   476.8  2861.2
   511.3 2861.07   525.1 2858.38   556.4 2862.12   574.8  2861.2   580.5 2863.27
   604.5 2878.27   612.5 2884.93   624.5 2897.71   632.5 2903.09   702.5 2927.13
#Mann= 3 ,-1,0
       0      .1       0  283.19    .045       0  319.38      .1       0
Bank Sta=283.19,319.38
XS Rating Curve= 0 ,0
Exp/Cntr=0.3,0.1

Type RM Length L Ch R = 1 ,20834   ,383.8,388.4,394.5
XS GIS Cut Line= 2
2209677.50763339579333.6341669382208980.81628152579613.595050732
#Sta/Elev= 30
       0 2944.64    83.3 2925.49   109.2 2910.79   132.9 2899.47   165.2 2888.91
   188.3 2885.34   199.7 2881.38   252.8 2852.16   280.5 2850.46   303.2 2852.76
   337.7 2851.06   376.5 2852.09   393.7  2847.7   428.1 2848.12  437.022846.556
   477.3 2845.52   487.92846.557   518.7 2862.27   535.8  2874.1   557.5 2891.85
   570.5 2900.02   612.6  2915.9   630.2 2918.27   642.4 2921.79   669.6 2934.48
   680.3 2936.87   721.4 2954.52   734.3 2957.17   742.9 2963.19   750.8 2966.54
#Mann= 3 ,-1,0
       0      .1       0  437.02    .045       0   487.9      .1       0
Bank Sta=437.02,487.9
XS Rating Curve= 0 ,0
Exp/Cntr=0.3,0.1

Type RM Length L Ch R = 1 ,20446   ,416.8,418.4,420.5
XS GIS Cut Line= 2
2209465.19425889579077.200480109 2208887.3175158579172.380178971
#Sta/Elev= 30
       0 2903.26    29.4 2893.26    41.6 2891.39      74 2881.42    90.2 2879.11
   102.4 2875.45   106.4 2873.87   122.6 2862.81   134.8 2856.76     147 2847.97
   155.1 2844.47   219.9 2846.43   232.1 2845.43   248.3 2847.09   276.7 2845.86
   280.8 2845.15  287.992840.455   321.1 2839.07   331.3 2840.43   349.7 2841.87
   406.4 2839.93   414.5 2840.94   430.7 2847.33   459.1 2870.91   479.4    2883
   515.9 2898.61     528  2902.3   540.2 2909.69   552.4 2912.68   585.7 2934.38
#Mann= 3 ,-1,0
       0      .1       0  287.99    .045       0   331.3      .1       0
Bank Sta=287.99,331.3
XS Rating Curve= 0 ,0
Exp/Cntr(USF)=0,0
Exp/Cntr=0.3,0.1

Type RM Length L Ch R = 1 ,20028   ,412.1,395.6,375.7
XS GIS Cut Line= 2
 2209453.8360671578733.9403338752208801.20255017578784.862833606
#Sta/Elev= 30
       0 2931.72     105 2893.12   178.2 2872.49   214.3 2865.05     242 2854.73
   254.4 2848.11   266.5 2847.37   274.5 2845.17   286.5 2839.01   310.6 2834.57
   322.6 2836.66   338.7  2835.7   382.8 2836.76   390.8 2834.99   422.9 2835.89
  434.422832.384   447.4 2831.41  479.752832.383   487.1 2836.12   491.1 2836.79
   511.2 2835.18   515.2 2836.03   521.9 2840.47   543.3 2859.07   571.4 2878.89
   583.4 2883.28   591.5 2891.34   595.5 2893.96   611.5 2903.16   654.6 2920.32
#Mann= 3 ,-1,0
       0      .1       0  434.42    .045       0  479.75      .1       0
#XS Ineff= 2 , 0
          324.48 2846.83
Permanent Ineff=
       F       F
Bank Sta=434.42,479.75
XS Rating Curve= 0 ,0
Exp/Cntr=0.3,0.1

Type RM Length L Ch R = 1 ,19632   ,368.6,369.6,364.7
XS GIS Cut Line= 3
2209069.40108672577992.2203714922209039.72878233578198.907454961
2208697.34256466578586.526219297
#Sta/Elev= 30
       0 2898.26    73.7 2875.79    85.8  2875.1   110.1 2868.04   134.3 2865.31
   175.1 2863.34   182.8 2860.31     203 2848.56   211.8 2846.48   243.9  2844.2
   259.9 2844.99   270.5 2841.25   318.6 2837.44   339.9 2832.77   371.6 2830.97
     400  2832.5     452 2825.85   461.9 2825.73   490.7 2825.11  511.08 2825.76
   521.4 2828.07   548.1 2828.59   558.7 2831.68   600.9 2838.81     613 2845.35
   632.3  2858.2   686.8 2885.65   711.7 2900.52   720.2 2902.54     726 2906.37
#Mann= 3 ,-1,0
       0      .1       0   461.9    .045       0  511.08      .1       0
Bank Sta=461.9,511.08
XS Rating Curve= 0 ,0
Exp/Cntr=0.3,0.1

Type RM Length L Ch R = 1 ,19262   ,441.4,446.2,446.7
XS GIS Cut Line= 2
2208897.24686449 577898.794039612208433.05557904578362.529949268
#Sta/Elev= 30
       0 2906.46    44.9 2892.15    58.1 2890.17    93.9 2879.29   122.2 2867.18
   133.5  2865.7     158 2847.91   182.4 2833.72   190.1 2831.59   212.8 2832.95
   227.7 2820.34   233.3 2819.09   255.9 2821.62   284.2 2820.01   306.8 2821.79
   347.5  2821.2   365.6 2825.67   382.6 2822.61   435.2 2824.81   466.3  2822.4
   473.1 2820.31   501.4 2820.34   512.7 2822.52   524.1 2830.21     537 2849.49
   544.3 2857.53   562.5 2870.81   578.2 2877.25   641.7 2911.46   656.1 2917.42
#Mann= 3 ,-1,0
       0      .1       0   473.1    .045       0   501.4      .1       0
Bank Sta=473.1,501.4
XS Rating Curve= 0 ,0
Exp/Cntr=0.3,0.1

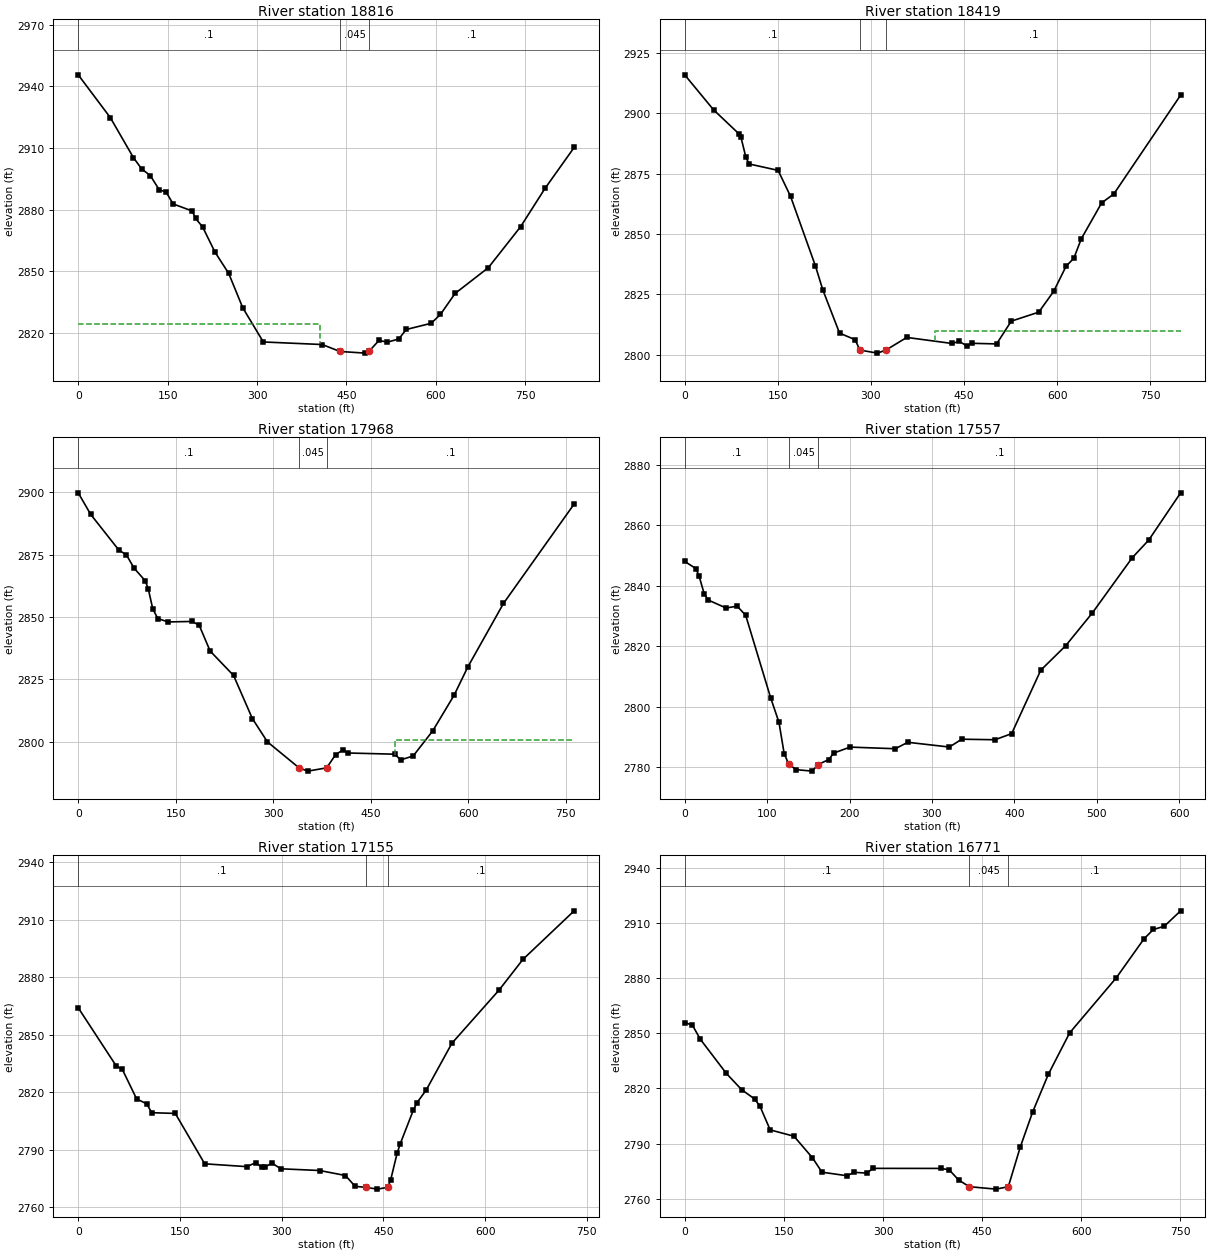
Type RM Length L Ch R = 1 ,18816   ,428,397.3,386.2
XS GIS Cut Line= 4
2208706.98213551577620.9184517082208473.08885337577765.441931903
2208212.67474554577954.0800335452208167.04424878578185.238937464
#Sta/Elev= 30
       0 2945.66    53.8 2924.84    92.6 2905.33   106.7 2899.73   120.9 2896.59
   135.9 2889.67   147.5 2888.52   159.2 2882.74   191.4 2879.29   196.9 2875.66
   208.6 2871.61   229.3 2859.36   252.5 2848.88   276.1 2832.12   310.6 2815.48
   409.4 2814.23   439.1 2810.85   481.6 2810.04  487.87 2810.88   504.6 2816.22
   518.9  2815.4   537.8 2816.93   550.4 2821.56   592.2 2824.58   607.8  2828.9
   632.3 2839.12   688.1 2851.68   742.4  2871.7   783.1 2890.27   832.1 2910.27
#Mann= 3 ,-1,0
       0      .1       0   439.1    .045       0  487.87      .1       0
#XS Ineff= 2 , 0
          406.13 2824.37
Permanent Ineff=
       F       F
Bank Sta=439.1,487.87
XS Rating Curve= 0 ,0
Exp/Cntr=0.3,0.1

Type RM Length L Ch R = 1 ,18419   ,467,450.9,443.6
XS GIS Cut Line= 3
2207966.71423766577390.7013391222207967.92694847 577970.39655335
2207995.74199444578187.945931903
#Sta/Elev= 30
       0 2915.84    46.5 2901.37    87.8 2891.33    90.5 2890.19    98.5 2881.83
   103.7 2878.96   150.5  2876.3   170.5 2865.59   210.5 2836.87   222.5 2826.88
   249.5 2808.96   274.5 2806.24  282.362801.936   310.5 2800.67  324.282801.937
   357.8 2807.17   430.5 2804.67   442.5 2805.52   454.5 2803.65   462.5 2804.74
   502.5 2804.48   526.1 2813.89   570.5 2817.63   594.6 2826.28   614.6  2836.7
   626.9 2839.89     639    2848   671.8 2862.85   691.4 2866.54     799 2907.43
#Mann= 3 ,-1,0
       0      .1       0  282.36    .045       0  324.28      .1       0
#XS Ineff= 2 , 0
                        403.1203            2810
Permanent Ineff=
       F       F
Bank Sta=282.36,324.28
XS Rating Curve= 0 ,0
Exp/Cntr=0.3,0.1

Type RM Length L Ch R = 1 ,17968   ,418.3,410.8,405.8
XS GIS Cut Line= 3
2207393.44111327577637.0827400982207692.58567676578096.849581837
     2207832.441578259.689191805
#Sta/Elev= 30
       0 2899.73    19.2 2891.09    62.2  2876.9    74.3 2874.81      86 2869.54
   103.2 2864.46   107.7 2861.36   114.6 2853.37   122.4 2849.34   138.5 2847.99
   175.5 2848.19   186.2 2846.65     203 2836.33   239.1 2826.53     268 2809.26
   291.2 2799.92  339.872789.513   353.3  2788.2  382.392789.513   396.2 2794.85
   406.8 2796.58   415.7 2795.46   486.9 2794.99   496.4 2792.72   515.5 2794.28
   545.6 2804.35   578.6 2818.69   599.5 2829.92   654.4 2855.39   763.2 2895.25
#Mann= 3 ,-1,0
       0      .1       0  339.87    .045       0  382.39      .1       0
#XS Ineff= 2 , 0
                          487.51          2800.5
Permanent Ineff=
       F       F
Bank Sta=339.87,382.39
XS Rating Curve= 0 ,0
Exp/Cntr=0.3,0.1

Type RM Length L Ch R = 1 ,17557   ,412,405.5,406.7
XS GIS Cut Line= 2
2207149.44613988578102.6227094662207626.80066985 578468.88048683
#Sta/Elev= 30
       0 2848.03    13.5 2845.69    17.3 2843.37    23.7 2837.31    28.6 2835.27
    50.2 2832.64    63.7 2833.24      74 2830.24   104.3 2802.96   114.4 2794.85
   120.7 2784.52   126.4 2780.95   135.6 2779.21   154.7 2778.73   161.9 2780.91
   174.9 2782.56   180.6 2784.67   200.6 2786.67   255.5 2786.13   270.7 2788.26
   321.1 2786.69   336.2 2789.28   376.5  2789.1   396.7 2791.12     432 2812.08
   462.2 2820.16   494.5 2830.97     543 2849.25   563.1 2855.11   601.7  2870.7
#Mann= 3 ,-1,0
       0      .1       0   126.4    .045       0   161.9      .1       0
Bank Sta=126.4,161.9
XS Rating Curve= 0 ,0
Exp/Cntr(USF)=0,0
Exp/Cntr=0.3,0.1

Type RM Length L Ch R = 1 ,17155   ,385.7,386.6,388.8
XS GIS Cut Line= 2
2206937.02059691578338.5133795332207551.58819646578734.675912726
#Sta/Elev= 30
       0 2863.98    56.1 2833.58      65 2831.83    86.1 2816.43   100.9 2813.85
   108.5 2809.21   143.1 2808.83   186.5 2782.53   248.5 2781.06   261.8 2783.12
   270.3 2780.79     275 2780.71   285.5 2782.93   298.8 2779.93   355.9 2779.04
     394 2776.43   408.3 2770.76   423.8 2770.27   441.2 2769.32   456.2 2770.25
   460.6    2774   470.1 2787.95   474.9 2793.09   493.9 2810.38     499 2814.22
     513    2821     551 2845.48   620.6 2873.26   655.7 2889.24   731.2 2914.58
#Mann= 3 ,-1,0
       0      .1       0   423.8    .045       0   456.2      .1       0
Bank Sta=423.8,456.2
XS Rating Curve= 0 ,0
Exp/Cntr=0.3,0.1

Type RM Length L Ch R = 1 ,16771   ,390.4,398.6,412.5
XS GIS Cut Line= 3
2206734.19282488578494.9875649762206841.27507298578675.414706049
2207245.88480751      579033.622
#Sta/Elev= 30
       0  2855.8    11.8 2854.31    23.5 2846.78      63 2828.15    86.3 2819.26
   105.8 2814.26     114 2810.22   129.3 2797.46   165.3 2794.02   193.3 2782.29
   207.7 2774.47   245.7 2772.53   256.4 2774.41   275.5 2773.96   284.9 2776.55
   387.5 2776.52   400.1 2775.77   414.3 2770.26  430.532766.589     471 2765.27
  489.552766.589   507.5 2787.97   526.3 2807.12   550.3  2827.8   582.3 2850.14
     653 2880.14   694.8 2901.26     709 2906.34   725.4 2908.07   750.2 2916.48
#Mann= 3 ,-1,0
       0      .1       0  430.53    .045       0  489.55      .1       0
Bank Sta=430.53,489.55
XS Rating Curve= 0 ,0
Exp/Cntr=0.3,0.1

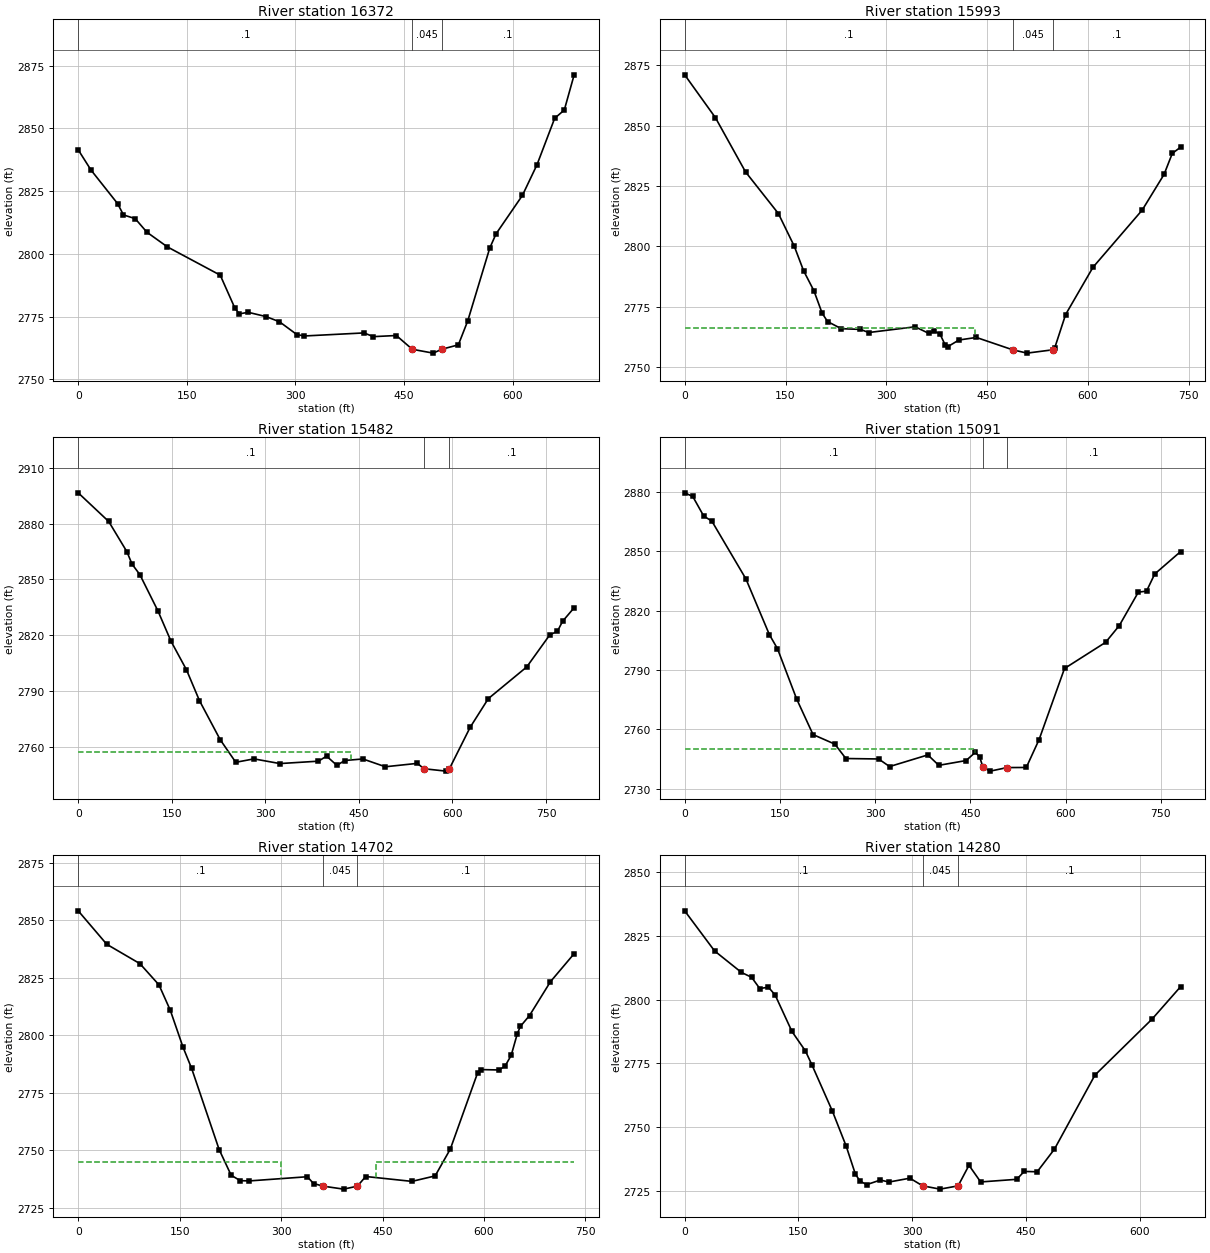
Type RM Length L Ch R = 1 ,16372   ,377.2,379.1,385.7
XS GIS Cut Line= 3
2206565.75912439578615.4666553172206599.37884984578827.013843102
2206782.65944615579260.458112586
#Sta/Elev= 30
       0 2841.42    17.6 2833.39    54.4 2819.99    62.5 2815.49    78.7    2814
    94.9 2808.59   123.2 2802.74   196.1 2791.49   216.5 2778.25   222.6 2776.08
   234.8 2776.69   259.2    2775   277.9 2772.93   301.9 2767.82   312.1 2767.26
   394.6 2768.48   407.6    2767   439.3 2767.45   461.3 2761.96   490.2 2760.43
  501.852761.962   524.9 2763.73   537.9  2773.3   568.3 2802.32     577 2807.97
   613.3 2823.24   633.5 2835.48   657.9 2853.98   671.2 2857.28   684.8  2871.3
#Mann= 3 ,-1,0
       0      .1       0   461.3    .045       0  501.85      .1       0
Bank Sta=461.3,501.85
XS Rating Curve= 0 ,0
Exp/Cntr=0.3,0.1

Type RM Length L Ch R = 1 ,15993   ,502,511,524.7
XS GIS Cut Line= 2
2206234.76066334578636.1817203632206370.73166171579361.360378354
#Sta/Elev= 30
       0 2871.12    45.8 2853.33    90.5 2830.89   139.4  2813.6   163.1 2800.02
   176.8 2789.94   192.3 2781.56   204.5 2772.28   212.6 2768.82     233 2765.86
   261.5 2765.57   273.7 2764.27   342.9 2766.65   363.2 2763.91   371.4 2764.72
   379.5 2763.81   387.6 2759.11   391.7 2758.45     408 2761.17   433.9 2762.23
  487.732757.132   509.3 2755.73  548.182757.132   550.5  2757.9   566.7 2771.72
   607.4 2791.31   680.7 2815.06   713.2 2829.85   725.4 2838.54   737.8 2841.14
#Mann= 3 ,-1,0
       0      .1       0  487.73    .045       0  548.18      .1       0
#XS Ineff= 2 , 0
        431.8613    2766
Permanent Ineff=
       F       F
Bank Sta=487.73,548.18
XS Rating Curve= 0 ,0
Exp/Cntr(USF)=0,0
Exp/Cntr=0.3,0.1

Type RM Length L Ch R = 1 ,15482   ,388.2,390.5,391.6
XS GIS Cut Line= 2
2205981.63184712578574.1925364882205763.94573417579338.947171503
#Sta/Elev= 30
       0 2896.59    48.9 2881.16      78 2864.93    86.3 2858.22    98.8 2852.57
   127.9 2832.97   148.7 2816.75   173.6  2801.3   194.4 2784.72   227.7 2763.67
   252.6 2751.54   281.8 2753.37   323.3 2750.85   385.2 2752.14   398.2 2754.86
   414.7 2749.88   427.3  2752.5   456.4 2753.33   492.4 2749.13   543.8 2750.96
  554.222748.076   589.4 2746.78  595.122748.075   628.4 2770.38   657.5 2785.81
   719.1 2802.87   755.9 2820.06   768.3  2822.1   776.7 2827.49   795.1 2834.74
#Mann= 3 ,-1,0
       0      .1       0  554.22    .045       0  595.12      .1       0
#XS Ineff= 2 , 0
        437.3022    2757
Permanent Ineff=
       F       F
Bank Sta=554.22,595.12
XS Rating Curve= 0 ,0
Exp/Cntr=0.3,0.1

Type RM Length L Ch R = 1 ,15091   ,387.1,389.8,388.2
XS GIS Cut Line= 2
2205653.70610703578537.3679263422205364.46011421 579263.03383962
#Sta/Elev= 30
       0 2879.62    12.7 2877.79    29.9 2867.92    42.9 2865.25    96.5 2836.04
   133.4 2807.89   146.2 2800.75   176.3 2775.37   202.2 2757.31   236.6 2752.47
   253.9  2745.2   305.5 2744.97   322.8 2741.13     383 2747.02   400.3 2741.75
   443.3 2744.17   457.9 2748.37   464.8 2745.83  470.012740.658   481.3 2738.82
   507.9 2740.62   538.1 2740.67   558.3 2754.81   598.3 2790.75     663 2803.97
   684.5  2812.4   714.6 2829.36   727.5 2829.89   740.4 2838.55   781.2 2849.91
#Mann= 3 ,-1,0
       0      .1       0  470.01    .045       0   507.9      .1       0
#XS Ineff= 2 , 0
        456.8939    2750
Permanent Ineff=
       F       F
Bank Sta=470.01,507.9
XS Rating Curve= 0 ,0
Exp/Cntr=0.3,0.1

Type RM Length L Ch R = 1 ,14702   ,423.5,421.4,422.5
XS GIS Cut Line= 2
2205339.99221239578428.1602141592205003.63099379579079.836337716
#Sta/Elev= 30
       0 2854.13    42.2 2839.58    91.2 2831.16   119.4 2821.93   136.2 2810.85
     155 2794.81   167.7 2785.61   208.4  2750.3   226.2 2739.11   239.7 2736.76
     253 2736.65   338.8 2738.47     348 2735.52  362.252734.369   392.5 2733.08
   412.82734.368   425.2 2738.57   493.5 2736.45   527.8 2738.83   550.3 2750.52
   590.8 2783.79   595.3 2785.08   622.3 2784.91   631.3 2786.62   640.3 2791.29
   649.3 2800.63   653.8 2803.83   667.4 2808.59   698.3 2823.29   733.4  2835.5
#Mann= 3 ,-1,0
       0      .1       0  362.25    .045       0   412.8      .1       0
#XS Ineff= 2 , 0
         299.399    2745  440.94            2745
Permanent Ineff=
       F       F
Bank Sta=362.25,412.8
XS Rating Curve= 0 ,0
Exp/Cntr=0.3,0.1

Type RM Length L Ch R = 1 ,14280   ,399.8,409.6,414.6
XS GIS Cut Line= 2
2204952.74023142 578241.669209172204669.85322848 578831.07294696
#Sta/Elev= 30
       0 2834.74    39.4 2819.05    74.9 2810.62    88.2 2808.74      99 2804.33
   110.4 2804.86   119.3 2801.77   141.4 2787.54   159.2  2779.9   168.1 2774.23
   194.7 2756.38   212.9 2742.67   224.9 2731.84   230.9 2729.04   239.9 2727.59
   257.9 2729.39   269.4 2728.62   296.9 2730.12  313.742727.122   336.7 2725.84
  360.492727.121   374.8 2735.17   390.2 2728.65   437.8 2729.68   447.6 2732.77
   464.7 2732.63   487.5  2741.5   540.8 2770.44   616.2 2792.39   653.8 2805.07
#Mann= 3 ,-1,0
       0      .1       0  313.74    .045       0  360.49      .1       0
#XS Ineff= 2 , 0
                        374.5034            2735
Permanent Ineff=
       F       F
Bank Sta=313.74,360.49
XS Rating Curve= 0 ,0
Exp/Cntr=0.3,0.1

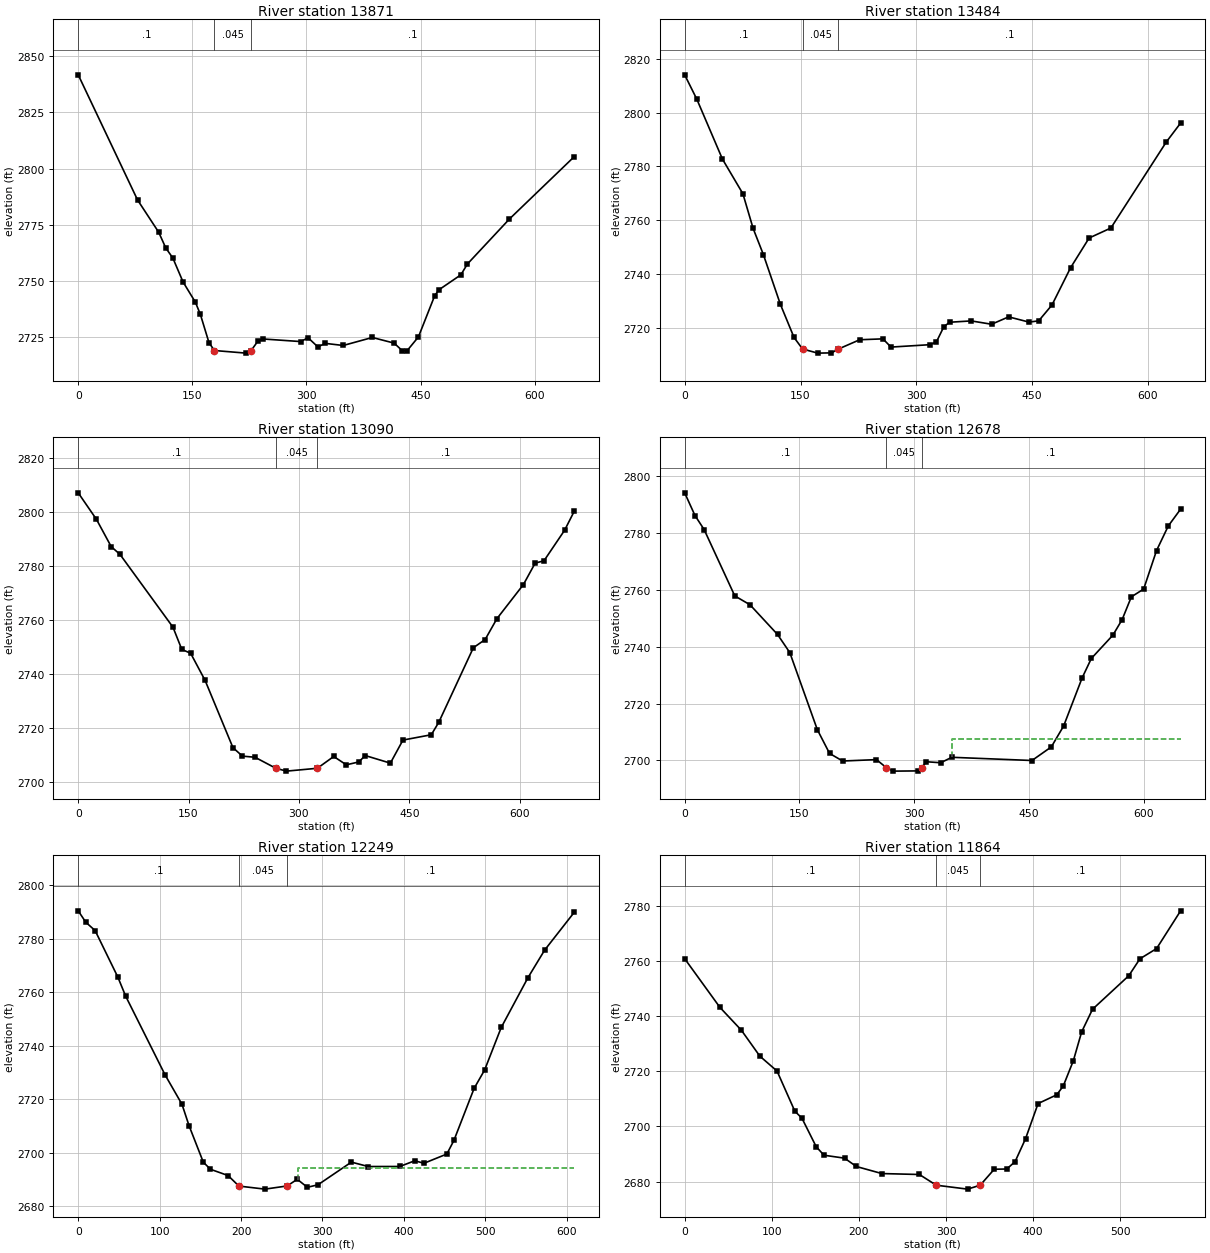
Type RM Length L Ch R = 1 ,13871   ,394.9,386.8,379.5
XS GIS Cut Line= 4
2204633.33841766578113.8320284872204561.12212439578237.294830439
2204352.78846257578453.7092787412204276.56669886578647.727153192
#Sta/Elev= 30
       0 2841.75      78  2786.1   105.8 2771.75   115.1 2764.76   124.4 2760.28
   137.8 2749.64     154 2740.65   160.6 2735.19   171.9 2722.65     179 2719.15
   220.6 2717.99  227.112719.053   236.7 2723.57   242.8 2724.29   292.8 2723.12
     302 2724.88     315 2720.77   324.7 2722.33   348.3 2721.39   386.6 2724.95
   415.2 2722.45     426 2719.07   432.2 2719.03   447.2  2725.2   468.6 2743.53
   474.3 2746.19     503 2752.81   511.6 2757.63   566.9 2777.66   651.9 2805.32
#Mann= 3 ,-1,0
       0      .1       0     179    .045       0  227.11      .1       0
Bank Sta=179,227.11
XS Rating Curve= 0 ,0
Exp/Cntr=0.3,0.1

Type RM Length L Ch R = 1 ,13484   ,412.9,394.3,373.9
XS GIS Cut Line= 3
2204248.80489298577952.8203960962204053.31587005578373.293051413
2204038.18420655578551.114678558
#Sta/Elev= 30
       0 2814.12    15.8    2805    48.9 2782.75    75.4 2769.85    88.6 2756.97
   101.9 2747.22   123.9 2728.72   141.6 2716.36  152.662712.065   172.3 2710.53
   190.1 2710.63  199.172712.065   226.6 2715.51   256.7 2715.84   267.2 2712.78
     318 2713.68     326 2714.73   335.6 2720.36   343.1 2722.03   371.1 2722.52
   397.4 2721.28   419.5 2724.03   445.9 2722.08   458.4 2722.54   475.6 2728.44
   499.7 2742.31   523.7 2753.38   551.9  2757.1   623.7 2789.14   642.2 2796.17
#Mann= 3 ,-1,0
       0      .1       0  152.66    .045       0  199.17      .1       0
Bank Sta=152.66,199.17
XS Rating Curve= 0 ,0
Exp/Cntr=0.3,0.1

Type RM Length L Ch R = 1 ,13090   ,395,411.9,435.5
XS GIS Cut Line= 4
2203769.47287955577872.4332606952203763.35418462 578060.07323845
 2203873.4906933578349.6914649852203873.71731163 578526.22714454
#Sta/Elev= 30
       0 2807.17    24.8 2797.33    44.8 2787.25    56.8 2784.34   128.8 2757.37
   140.8 2749.13   152.8 2747.71   172.5 2737.62   210.3 2712.73   223.2 2709.58
   240.3 2709.16  268.652705.078   283.1 2704.02  325.042705.078   347.3 2709.45
   364.4 2706.36   381.4 2707.42   390.1  2709.8   424.3 2706.98   441.4 2715.53
   479.9  2717.5     490 2722.07   537.1 2749.76   553.1 2752.79   569.1 2760.52
   605.1 2773.16   621.1 2781.12   633.1 2781.98   661.1 2793.29   674.1 2800.27
#Mann= 3 ,-1,0
       0      .1       0  268.65    .045       0  325.04      .1       0
Bank Sta=268.65,325.04
XS Rating Curve= 0 ,0
Exp/Cntr(USF)=0,0
Exp/Cntr=0.3,0.1

Type RM Length L Ch R = 1 ,12678   ,450.1,428.6,386.5
XS GIS Cut Line= 4
2203460.45645171 577875.828373172203459.10040654578070.456756781
2203343.20379965578317.0584253762203362.87980751578497.194107025
#Sta/Elev= 30
       0 2794.15    13.5 2786.15    25.4 2781.23    65.5 2757.87    85.4 2754.75
   121.4 2744.29   137.4 2737.93   173.4 2710.79   189.4 2702.43   206.5 2699.76
   250.7 2700.25  263.462697.455   272.8  2696.2     305 2696.28  309.792697.454
   316.1  2699.5   334.7 2699.15   349.2 2701.07     454 2699.94   479.3 2704.73
   495.4  2712.1   519.5 2728.98   531.6 2735.86   559.8 2744.07   571.9 2749.56
   583.9 2757.54     600 2760.29   616.8 2773.82   632.2  2782.5   648.3 2788.41
#Mann= 3 ,-1,0
       0      .1       0  263.46    .045       0  309.79      .1       0
#XS Ineff= 2 , 0
                          349.43         2707.55
Permanent Ineff=
       F       F
Bank Sta=263.46,309.79
XS Rating Curve= 0 ,0
Exp/Cntr=0.3,0.1

Type RM Length L Ch R = 1 ,12249   ,381.8,385.5,390.6
XS GIS Cut Line= 4
2202923.72239542577996.6664864382202989.73153649578145.341039609
2203173.91990667 578347.651900012203211.12087561 578516.60675122
#Sta/Elev= 30
       0  2790.5     9.3 2786.24    20.8  2783.1    48.7 2765.71    58.3 2758.59
   106.8  2729.1   127.5 2718.14   136.2 2710.12   153.7 2696.49   162.5 2693.84
   184.1  2691.5  197.432687.564   229.4 2686.42  256.79 2687.61   269.1 2690.11
   281.5 2687.11   294.5 2688.03   335.6 2696.52   356.4 2694.87   395.1 2694.89
   413.5 2697.03   424.8 2696.09   452.9 2699.55   461.6 2704.65   486.4  2724.1
   499.3 2730.97   519.7 2746.87   552.5 2765.48     573 2775.79   609.3 2789.91
#Mann= 3 ,-1,0
       0      .1       0  197.43    .045       0  256.79      .1       0
#XS Ineff= 2 , 0
                          269.73         2694.33
Permanent Ineff=
       F       F
Bank Sta=197.43,256.79
XS Rating Curve= 0 ,0
Exp/Cntr=0.3,0.1

Type RM Length L Ch R = 1 ,11864   ,417.9,428.4,441
XS GIS Cut Line= 3
2202613.37098499578141.5494239022202646.02418458578294.586972625
2202871.41727436578640.363411542
#Sta/Elev= 30
       0 2760.76    40.5  2743.1    65.1 2734.83    86.3 2725.44     106 2720.05
   126.4 2705.53   134.6 2702.95     151 2692.61   159.9 2689.55   183.5 2688.49
     197 2685.47   226.3 2682.91   269.4 2682.57  288.722678.691   324.7 2677.27
  339.182678.692   355.3 2684.48   369.7 2684.56   379.2 2687.23   391.2 2695.52
   405.6 2708.27     427 2711.44   434.5 2714.63   446.1 2723.81   455.6 2734.23
   468.1 2742.44   509.7 2754.58   522.5 2760.72   541.6 2764.42   569.2  2778.1
#Mann= 3 ,-1,0
       0      .1       0  288.72    .045       0  339.18      .1       0
Bank Sta=288.72,339.18
XS Rating Curve= 0 ,0
Exp/Cntr=0.3,0.1

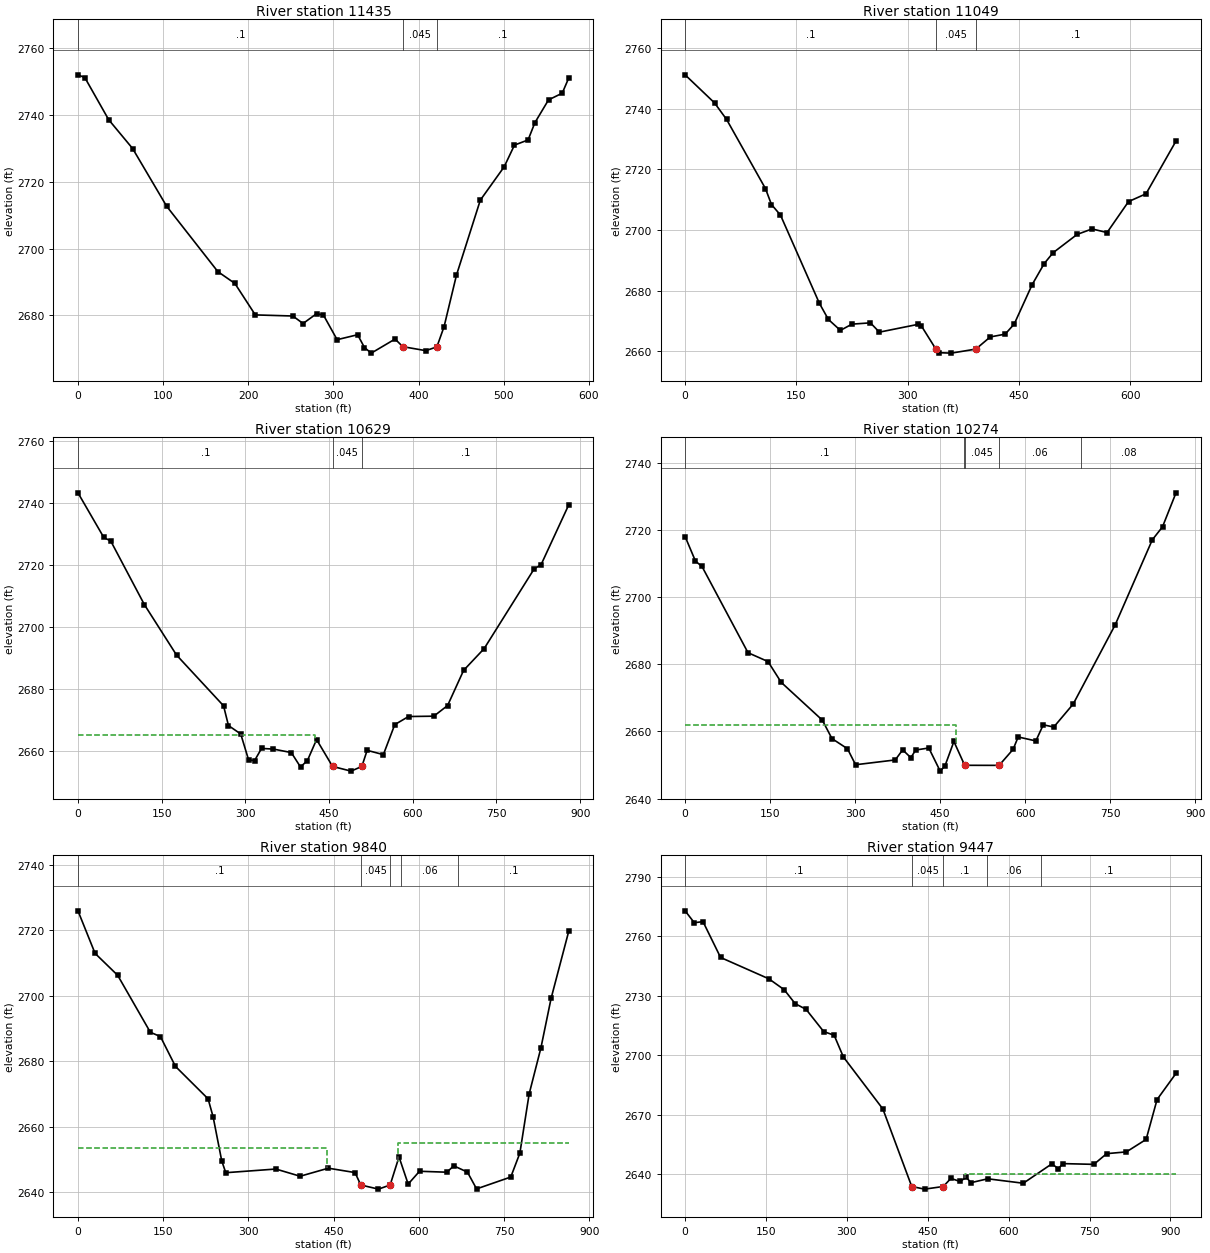
Type RM Length L Ch R = 1 ,11435   ,383,386.4,388
XS GIS Cut Line= 2
2202320.53443391578185.0967306442202348.72116456578760.983456282
#Sta/Elev= 30
       0 2752.07     8.1 2751.23    36.1 2738.62    64.2 2729.99   104.2 2712.69
   164.3 2693.12   184.3 2689.58   208.3 2680.15   252.4 2679.82   264.4 2677.57
   280.4 2680.54   288.4 2680.07   304.4 2672.73   328.5 2674.21   336.5 2670.38
   344.5  2668.7   372.5 2672.92   381.5 2670.64   408.6 2669.44   421.6 2670.58
     430 2676.61   444.6 2692.08   472.6 2714.53   500.7 2724.55   512.7 2731.02
   528.7 2732.56   536.7 2737.73   552.7 2744.56   568.8 2746.57   576.6 2751.21
#Mann= 3 ,-1,0
       0      .1       0   381.5    .045       0   421.6      .1       0
Bank Sta=381.5,421.6
XS Rating Curve= 0 ,0
Exp/Cntr=0.3,0.1

Type RM Length L Ch R = 1 ,11049   ,417,419.3,422.5
XS GIS Cut Line= 2
2202018.08166496578137.8448942312201928.13684954578793.157120891
#Sta/Elev= 30
       0 2751.18    39.7 2741.91    55.9 2736.46   108.3 2713.65   116.4 2708.39
   128.5 2704.92     181 2675.79   193.1 2670.48   209.3 2666.88   224.8 2668.94
   249.7 2669.37   261.8  2666.3   314.3 2668.89   318.3 2668.39   337.92660.714
   342.5 2659.52   358.7 2659.38   391.82660.715   411.2 2664.72   431.3 2665.64
   443.5 2668.98   467.7 2681.99   483.9 2688.92   495.9  2692.5   528.2 2698.53
   548.4 2700.35   568.6 2699.15   597.5 2709.36   621.1 2711.94   661.5 2729.34
#Mann= 3 ,-1,0
       0      .1       0   337.9    .045       0   391.8      .1       0
Bank Sta=337.9,391.8
XS Rating Curve= 0 ,0
Exp/Cntr(USF)=0,0
Exp/Cntr=0.3,0.1

Type RM Length L Ch R = 1 ,10629   ,342.4,355.2,364.5
XS GIS Cut Line= 4
2201772.57361849578003.0835660882201606.03197763578217.537680899
2201507.78250807578618.774315477 2201545.9546285578810.127142186
#Sta/Elev= 30
       0 2743.39    46.3 2728.95    58.8 2727.78   119.1 2707.19   176.7 2690.88
   260.9 2674.47   269.7 2668.08   291.7 2665.35   305.8 2656.95   316.5 2656.74
     329 2660.68   350.3 2660.46   382.3 2659.34   398.8 2654.67   411.2 2656.76
   427.6 2663.55  456.242654.855   489.4 2653.33  508.762654.851   518.2 2660.06
   547.3 2658.67   567.7 2668.38   592.4    2671   637.7 2671.11   662.4 2674.56
   691.1 2685.94   727.9 2692.98   817.6  2718.8   829.8 2720.09   879.7 2739.58
#Mann= 3 ,-1,0
       0      .1       0  456.24    .045       0  508.76      .1       0
#XS Ineff= 2 , 0
        425.2083    2665
Permanent Ineff=
       F       F
Bank Sta=456.24,508.76
XS Rating Curve= 0 ,0
Exp/Cntr=0.3,0.1

Type RM Length L Ch R = 1 ,10274   ,396.4,434.4,454.6
XS GIS Cut Line= 4
2201596.31100501577923.5902643512201364.60504678 578101.13272467
2201132.45741154578423.6164239022200974.92902002578504.260072421
#Sta/Elev= 30
       0 2717.99    18.3 2710.65    29.8 2709.07     111  2683.4   146.3 2680.76
   169.6 2674.57   242.1 2663.33   259.1 2657.84   286.5 2654.81   300.8 2650.05
   370.8 2651.48   383.9 2654.48   398.3 2652.16   406.9 2654.43     430 2655.04
   450.1 2648.15   458.5 2649.69   474.3 2656.97  493.342649.886  554.082649.862
   578.8 2654.64   587.7 2658.32   618.9 2657.14     632 2661.94   650.5 2661.27
   684.8 2668.12     759 2691.73   824.4 2717.01   842.4 2720.87   866.2 2730.99
#Mann= 5 ,-1,0
       0      .1       0  491.91     .06       0  493.34    .045       0
  554.08     .06       0  699.26     .08       0
#XS Ineff= 2 , 0
        477.3153    2662
Permanent Ineff=
       F       F
Bank Sta=493.34,554.08
XS Rating Curve= 0 ,0
Exp/Cntr=0.3,0.1

Type RM Length L Ch R = 1 ,9840    ,400.4,393,384.4
XS GIS Cut Line= 4
     2201571.341      577843.4792201337.07091961577954.284046427
2200814.08846394577912.403613483 2200736.1599002577893.986778039
#Sta/Elev= 30
       0 2725.98    30.1 2712.98    69.9 2706.27   127.4 2688.86   145.1 2687.55
   171.6 2678.43     229 2668.52   237.9 2662.98     253 2649.57   260.1 2645.94
   348.3 2647.06     391 2644.86   440.6 2647.32   487.6 2645.98  497.682642.186
   528.9 2640.92  549.412642.194     565 2650.77   581.1 2642.46   601.1 2646.38
   649.3 2646.09   661.3 2648.05   685.4 2646.12   701.5 2640.99   761.7 2644.62
   777.7 2651.93     794    2670   814.7 2684.07   832.6 2699.19   863.9 2719.88
#Mann= 5 ,-1,0
       0      .1       0  497.68    .045       0  549.41      .1       0
  569.15     .06       0  669.15      .1       0
#XS Ineff= 2 , 0
          439.02 2653.64562.3633            2655
Permanent Ineff=
       F       F
Bank Sta=497.68,549.41
XS Rating Curve= 0 ,0
Exp/Cntr=0.3,0.1

Type RM Length L Ch R = 1 ,9447    ,447.1,434.5,423.7
XS GIS Cut Line= 2
2201580.85743391577467.7553815122200685.70943391577633.661381512
#Sta/Elev= 30
       0 2772.87      17 2766.88    33.2 2767.41    65.8 2749.35   155.3 2738.59
   183.8 2733.09   204.1 2726.06   224.4 2723.18     257 2711.98   276.4 2710.14
   293.5 2699.19   366.8 2672.93  420.322633.853   444.1 2632.53  478.832633.852
   492.9 2637.94   509.7  2636.4   521.4 2638.44   530.3 2635.79   561.2 2637.74
   627.2  2635.5   680.1 2645.27   692.3 2642.83   700.4  2645.4   758.1 2645.02
   781.8 2650.42   818.4 2651.31     855  2657.6   875.3 2677.71   910.4 2690.89
#Mann= 5 ,-1,0
       0      .1       0  420.32    .045       0  478.83      .1       0
     560     .06       0     660      .1       0
#XS Ineff= 1 ,-1
 519.195 910.393    2640
Permanent Ineff=
       F
Bank Sta=420.32,478.83
XS Rating Curve= 0 ,0
Exp/Cntr=0.3,0.1