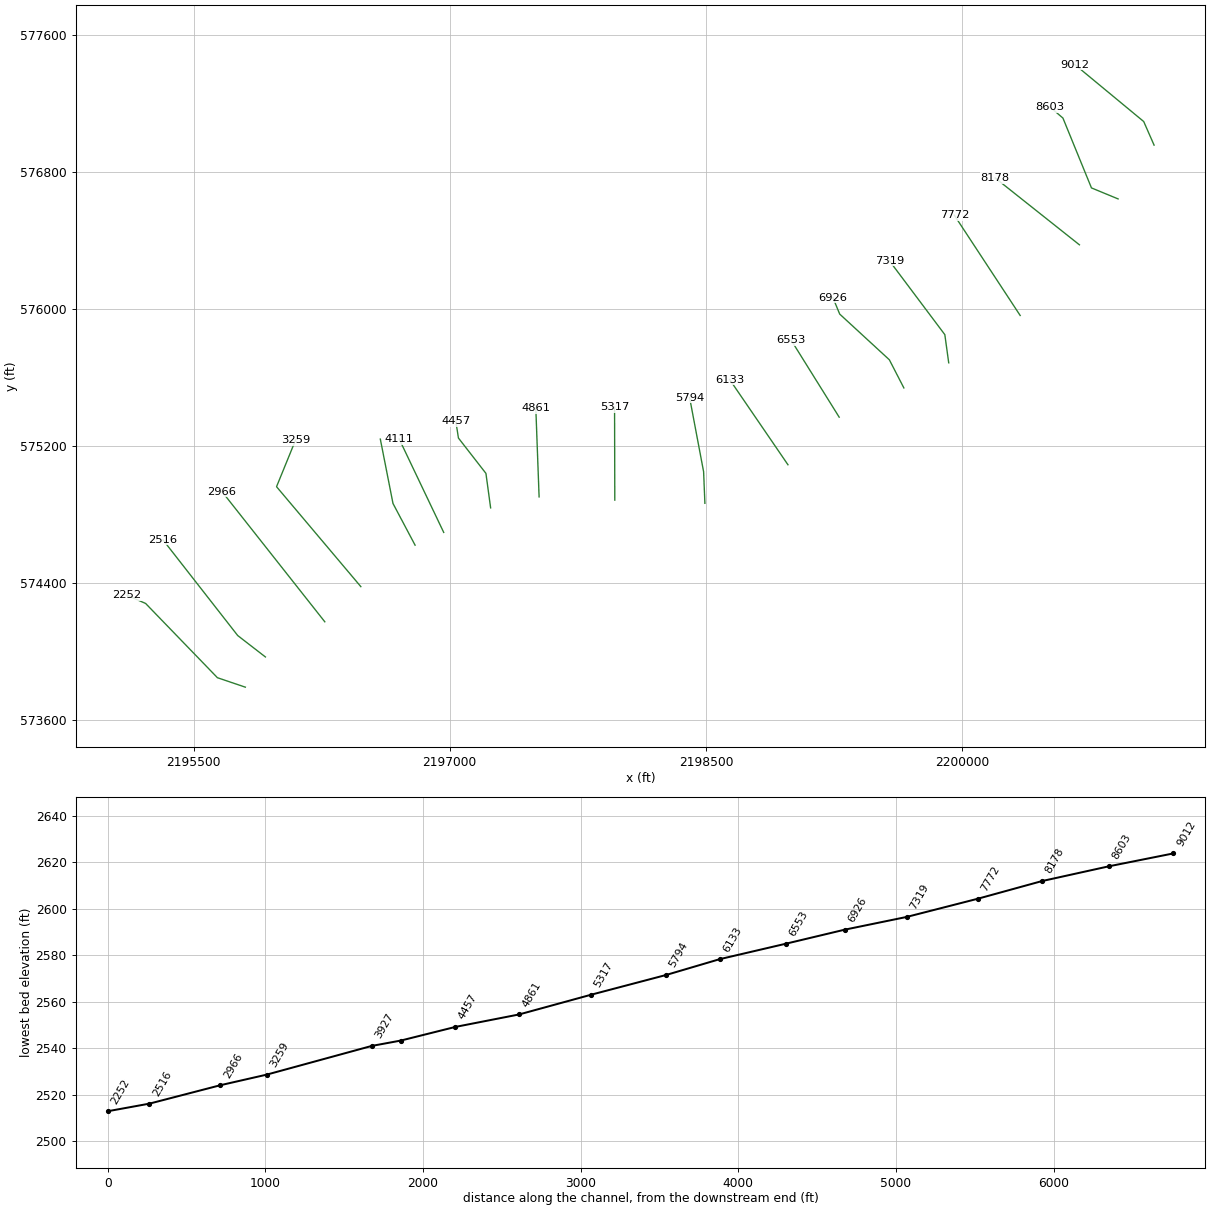
HEC-RAS study BFKELKRV.prj: BFKELKRV

--- BFKELKRV.g01 (geometry) --- (continued)

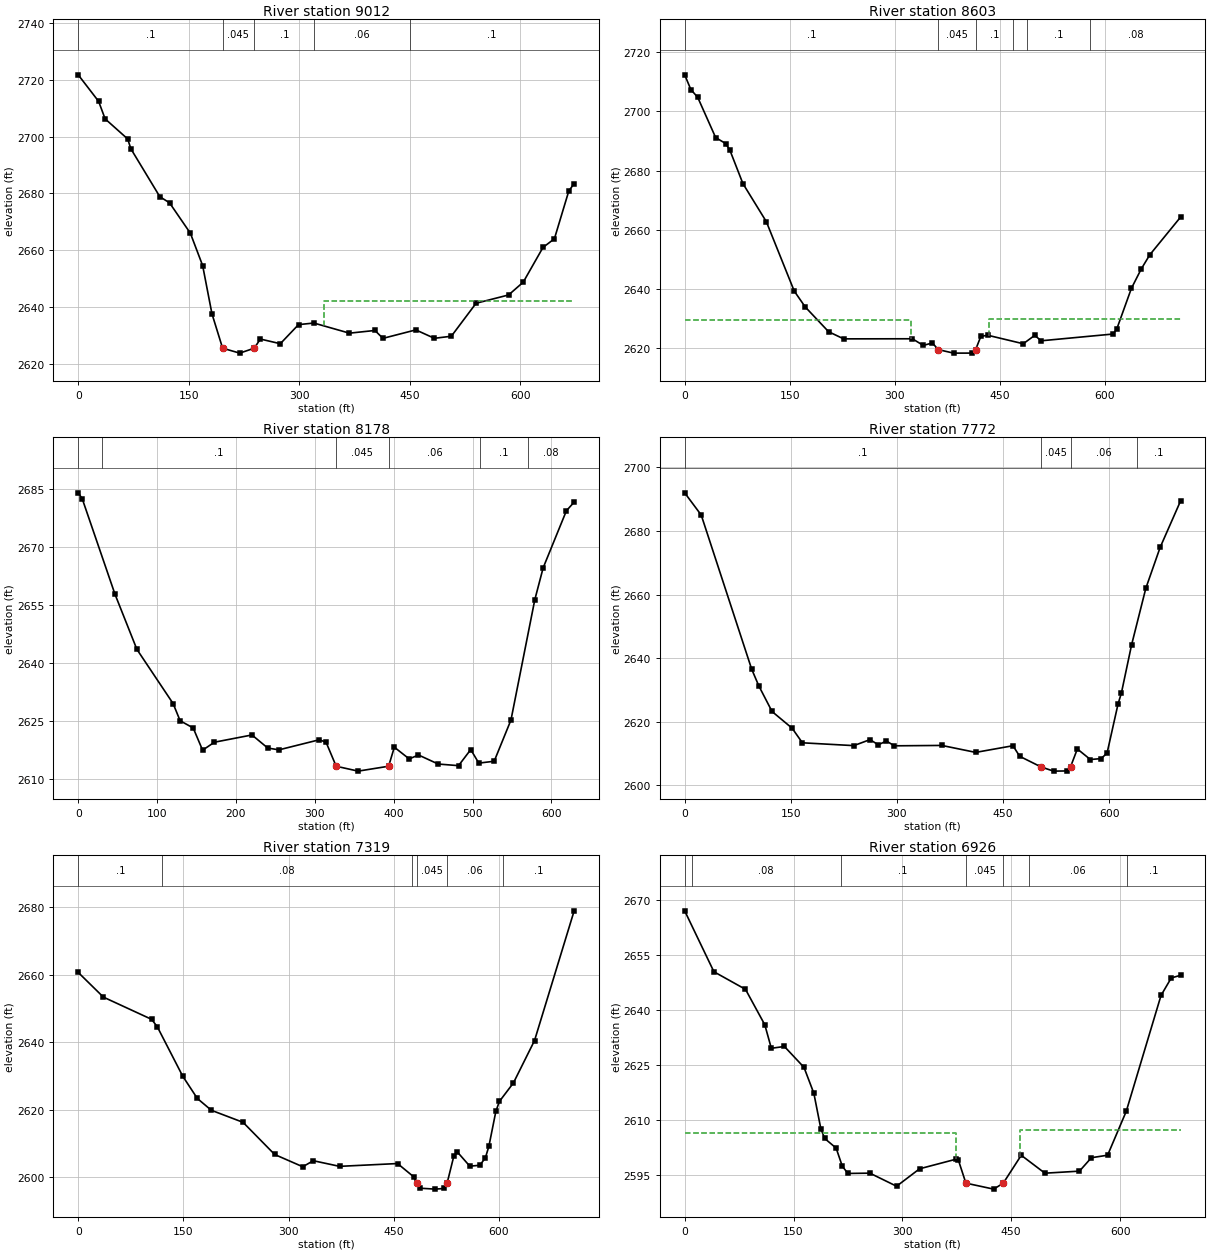
Type RM Length L Ch R = 1 ,9012    ,423.1,409.8,400.5
XS GIS Cut Line= 3
 2201123.5715237576955.7977903992201062.89076302577093.386254341
2200659.52507978577425.808561083
#Sta/Elev= 30
       0 2721.71    27.7 2712.38    36.5 2706.23    67.1 2699.17    71.5 2695.69
   110.8 2678.85   123.9 2676.72   152.2 2666.03   168.9 2654.63   181.5 2637.71
  195.982625.594   219.2 2623.86  238.932625.595   247.2 2628.81   274.3 2627.17
     299 2633.88   319.8 2634.44   368.1 2630.88   402.7 2631.83   413.6 2629.05
   458.2 2632.03   483.4 2629.07   506.4  2629.8     540  2641.4   584.1 2644.31
     604 2648.81   630.8 2661.02   646.3 2664.07   665.8 2680.84   673.1  2683.5
#Mann= 5 ,-1,0
       0      .1       0  195.98    .045       0  238.93      .1       0
  320.38     .06       0  450.38      .1       0
#XS Ineff= 2 , 0
                           333.5         2642.31
Permanent Ineff=
       F       F
Bank Sta=195.98,238.93
XS Rating Curve= 0 ,0
Exp/Cntr=0.3,0.1

Type RM Length L Ch R = 1 ,8603    ,405,424.6,433.1
XS GIS Cut Line= 4
2200913.04536118576641.8239846292200757.01864055576706.070281361
2200589.97826905577113.5753634852200514.71832145577177.821660217
#Sta/Elev= 30
       0 2712.35     8.8 2707.39    18.6 2704.75    44.2 2691.16    58.4 2689.14
    64.5 2686.92    83.1 2675.62   116.6 2662.73   156.4 2639.29   172.1 2633.92
   205.5 2625.54     227 2623.13   325.1 2623.16   340.7 2620.91   353.7 2621.76
  361.892619.514   383.9 2618.31   409.9 2618.32  415.462619.517   422.8 2623.94
   432.4 2624.37   483.4 2621.48   499.8 2624.31     509 2622.48   611.5 2624.76
   616.8 2626.37   637.8 2640.18   651.7 2646.67   664.1 2651.54   708.1 2664.29
#Mann= 6 ,-1,0
       0      .1       0  361.89    .045       0  415.46      .1       0
  468.74     .06       0  488.74      .1       0  578.74     .08       0
#XS Ineff= 2 , 0
          323.48 2629.58435.1539            2630
Permanent Ineff=
       F       F
Bank Sta=361.89,415.46
XS Rating Curve= 0 ,0
Exp/Cntr(USF)=0,0
Exp/Cntr=0.3,0.1

Type RM Length L Ch R = 1 ,8178    ,426.2,405.7,402.3
XS GIS Cut Line= 2
2200686.54084545576374.046142186 2200193.3444713 576764.10494525
#Sta/Elev= 30
       0 2684.13     5.1 2682.59    46.6 2657.84    74.4 2643.53   120.3 2629.48
   129.2 2625.02   145.8 2623.14   157.7 2617.38   172.7 2619.45   220.3 2621.33
   240.3 2617.94   254.5 2617.47   305.8 2620.09   314.3 2619.42  327.07 2613.22
   354.9 2611.95  393.58 2613.22   400.8 2618.16   419.7 2615.11   431.4 2616.14
   456.4 2613.79   482.2 2613.37   497.7 2617.54   507.9 2614.03   527.4 2614.51
   548.7 2625.22   578.9  2656.4   589.5 2664.68     619 2679.49   628.8 2681.72
#Mann= 6 ,-1,0
       0     .08       0      30      .1       0  327.07    .045       0
  393.58     .06       0     510      .1       0     570     .08       0
Bank Sta=327.07,393.58
XS Rating Curve= 0 ,0
Exp/Cntr=0.3,0.1

Type RM Length L Ch R = 1 ,7772    ,451.8,452.9,454.3
XS GIS Cut Line= 2
2200339.73248131575961.668750664 2199953.9969476 576547.09090286
#Sta/Elev= 30
       0 2692.02    23.4 2685.02    94.6 2636.56   104.8 2631.22   123.5 2623.16
   151.9 2617.89   166.4  2613.3   239.1 2612.41   262.1 2614.31   273.6 2612.67
   285.2 2613.86   296.4 2612.35   363.5 2612.47   411.4 2610.28   464.1 2612.38
   473.6 2609.05  503.822605.697   521.5 2604.38   540.7 2604.44  545.442605.698
   555.1 2611.36   573.5 2608.04   588.6 2608.32   597.1 2610.04   612.6 2625.48
   617.4    2629   631.7 2644.07   651.9 2661.95   672.1 2674.81   701.1  2689.5
#Mann= 4 ,-1,0
       0      .1       0  503.82    .045       0  545.44     .06       0
     640      .1       0
Bank Sta=503.82,545.44
XS Rating Curve= 0 ,0
Exp/Cntr=0.3,0.1

Type RM Length L Ch R = 1 ,7319    ,388.9,393.2,397.5
XS GIS Cut Line= 3
2199921.27483544575685.5773591422199898.55258846575849.971035035
2199572.95494259576282.364548723
#Sta/Elev= 30
       0 2660.74    35.9 2653.42   104.6 2646.84   112.7 2644.66     149    2630
   169.9 2623.38   189.9 2619.88   235.1 2616.31   280.1 2606.79   320.2 2603.15
   335.2 2604.94   372.7 2603.27   455.4  2604.1   478.4 2600.17  482.982598.292
     487  2596.8     509 2596.52   521.3 2596.71  526.042598.287   535.5 2606.21
   540.5 2607.56   558.4 2603.32   572.7 2603.59   580.6 2605.79   585.6 2609.21
   595.6  2619.6   600.6 2622.51   620.6 2627.99   650.7 2640.55   707.2 2678.99
#Mann= 6 ,-1,0
       0      .1       0     120     .08       0  475.96     .06       0
  482.98    .045       0  526.04     .06       0  605.96      .1       0
Bank Sta=482.98,526.04
XS Rating Curve= 0 ,0
Exp/Cntr=0.3,0.1

Type RM Length L Ch R = 1 ,6926    ,379.5,373.4,365.4
XS GIS Cut Line= 4
2199658.68887783575539.1358678242199573.75054106575703.270142186
2199283.02503268575969.9912816672199243.23554106576066.131920225
#Sta/Elev= 30
       0    2667    40.3 2650.37    83.8 2645.57   110.4  2635.9   119.4 2629.48
   137.4 2629.98   164.4 2624.28     178  2617.2   187.6 2607.55   192.9 2604.87
   208.7 2602.24   217.2  2597.3   224.9 2595.32   255.2  2595.4     292 2591.83
   323.7 2596.59   374.1 2599.22     377 2599.06  387.492592.674   425.8 2591.04
  438.972592.659   463.8 2600.28   496.4 2595.39     544 2595.95   560.4 2599.61
   582.8  2600.3   608.5 2612.29   656.4 2643.91   670.5 2648.68   683.4 2649.41
#Mann= 7 ,-1,0
       0      .1       0      10     .08       0  214.81      .1       0
  387.49    .045       0  438.97      .1       0  474.81     .06       0
  609.35      .1       0
#XS Ineff= 2 , 0
          373.33 2606.24  462.11         2607.29
Permanent Ineff=
       F       F
Bank Sta=387.49,438.97
XS Rating Curve= 0 ,0
Exp/Cntr=0.3,0.1

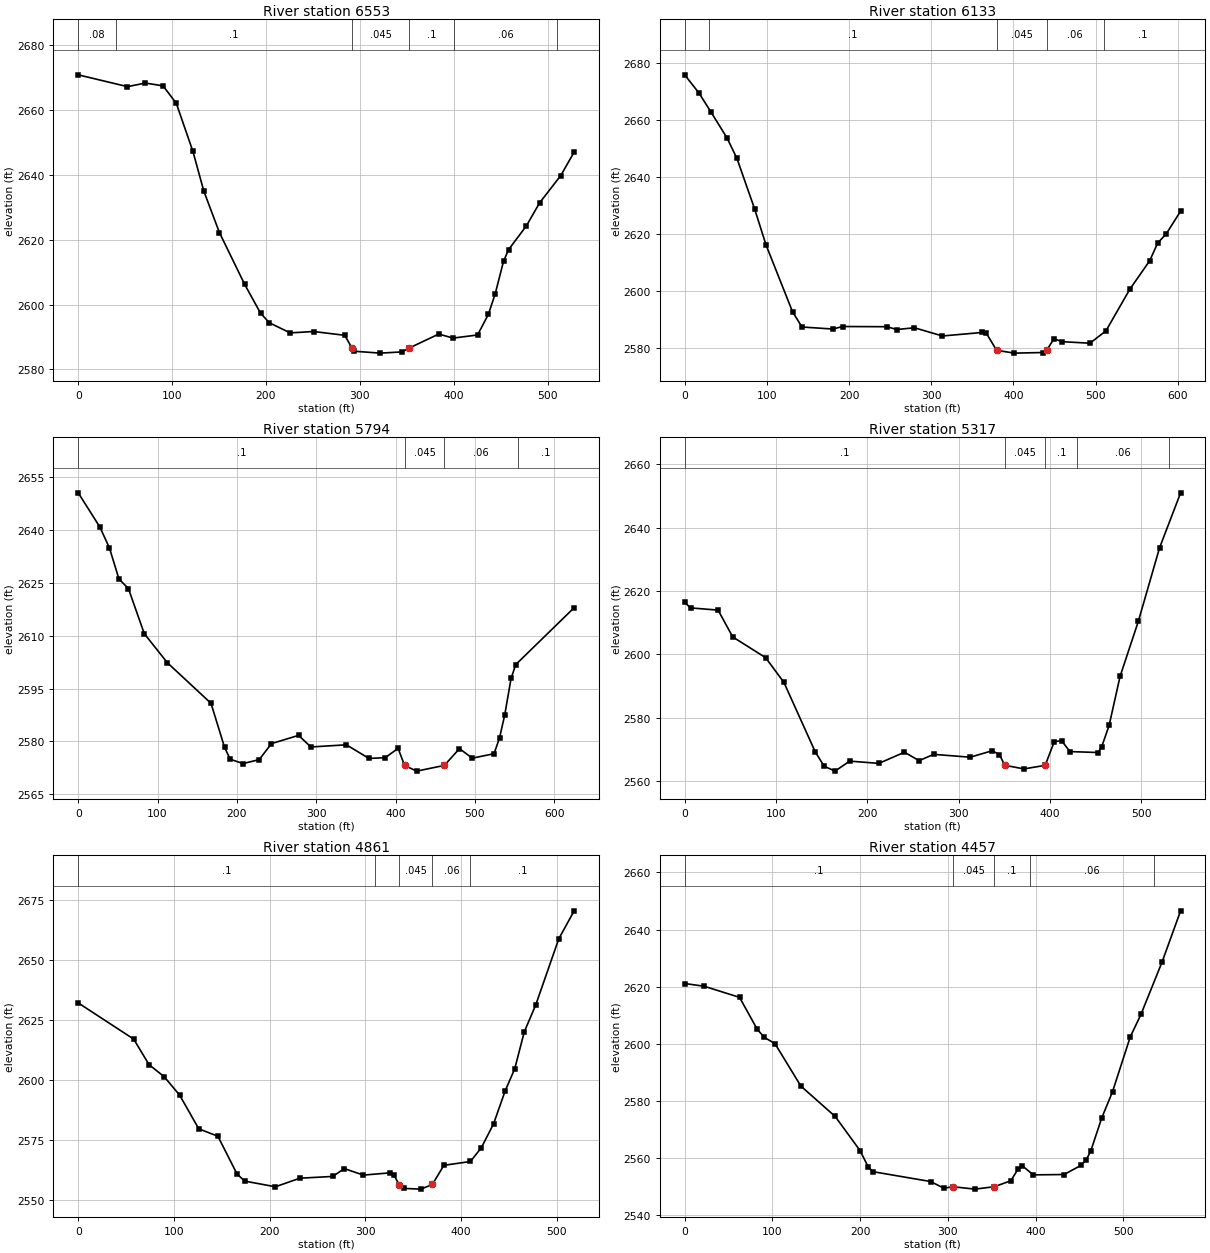
Type RM Length L Ch R = 1 ,6553    ,418.2,419.2,420.8
XS GIS Cut Line= 2
 2199279.9809002575368.5705834532198999.67935649575816.325840449
#Sta/Elev= 30
       0  2670.9    52.5 2667.25    71.5 2668.36    90.4  2667.5   104.5 2662.09
   122.2 2647.25   133.8 2635.01   150.4 2622.22   177.3 2606.23   194.2 2597.34
   203.6 2594.37   225.8 2591.25   250.8 2591.67   283.9  2590.5  291.742586.521
   293.4  2585.6   321.6    2585   345.2 2585.38  352.212586.522   384.1 2590.89
   399.2 2589.64   425.4  2590.6   436.9 2596.95   444.2 2603.31   453.1 2613.37
   458.5 2616.97   477.4 2624.27   491.5 2631.39     514  2639.8   528.3 2647.06
#Mann= 6 ,-1,0
       0     .08       0      40      .1       0  291.74    .045       0
  352.21      .1       0     400     .06       0     510      .1       0
Bank Sta=291.74,352.21
XS Rating Curve= 0 ,0
Exp/Cntr=0.3,0.1

Type RM Length L Ch R = 1 ,6133    ,348.9,339.3,325.9
XS GIS Cut Line= 2
2198980.14963381575090.7348206862198638.72645689575588.184718235
#Sta/Elev= 30
       0 2675.73    17.5 2669.32    32.1 2662.66    51.5 2653.66    63.6 2646.46
    85.2 2628.71    98.9 2616.26   131.2 2592.83   142.7  2587.5   180.1 2586.79
   192.2 2587.67   246.3  2587.6   257.8 2586.62   279.5 2587.23   313.5 2584.36
     362 2585.59   367.1 2585.24  379.452579.355   400.8 2578.36   436.2 2578.57
  440.252579.354   449.3 2583.38   459.4 2582.36     493 2581.83   512.4 2586.12
   541.5 2600.71   565.7 2610.68   575.4 2616.88   585.8 2620.09   603.3 2628.04
#Mann= 5 ,-1,0
       0     .08       0      30      .1       0  379.45    .045       0
  440.25     .06       0     510      .1       0
Bank Sta=379.45,440.25
XS Rating Curve= 0 ,0
Exp/Cntr(USF)=0,0
Exp/Cntr=0.3,0.1

Type RM Length L Ch R = 1 ,5794    ,481.4,477.3,472.6
XS GIS Cut Line= 3
2198493.83823197574865.9041745662198486.28730674 575050.29898764
2198404.23169326575483.223162206
#Sta/Elev= 30
       0 2650.57    27.3 2640.86    39.4  2634.9    51.3 2626.14    63.3 2623.38
    83.3 2610.59   112.4 2602.34   167.4 2590.82   184.5 2578.31   191.6 2574.95
   207.8 2573.71   228.2 2574.84   243.6 2579.38   277.8 2581.72   293.3 2578.43
   338.1 2579.04   366.6 2575.17     387  2575.4   403.3 2578.02   411.4 2573.19
   426.6 2571.57  461.612573.195   480.6 2577.95   496.8 2575.25   524.2 2576.51
   531.1 2580.99   537.6 2587.43   545.7 2597.91   551.6 2601.82   625.2 2617.96
#Mann= 4 ,-1,0
       0      .1       0   411.4    .045       0  461.61     .06       0
  554.55      .1       0
#XS Ineff= 2 , 0
        261.6414    2580
Permanent Ineff=
       F       F
Bank Sta=411.4,461.61
XS Rating Curve= 0 ,0
Exp/Cntr=0.3,0.1

Type RM Length L Ch R = 1 ,5317    ,454.9,455.4,456.1
XS GIS Cut Line= 2
2197966.32817957574884.5553815122197964.97339653575427.419685904
#Sta/Elev= 30
       0 2616.39     6.5 2614.65    36.6 2613.95    52.6 2605.47    88.6 2598.92
   108.6 2591.12   142.8 2569.21   152.6 2564.62   164.6 2563.05   180.6 2566.21
   212.6  2565.5   240.6 2569.03   256.6 2566.36   272.6 2568.35   312.6 2567.45
   336.6 2569.49   344.6 2568.28  350.272564.912   371.4 2563.75  394.652564.875
   404.6 2572.38   412.6 2572.67   421.7 2569.23   452.6 2568.93   456.6 2570.83
   464.6 2577.48   476.6 2592.97   496.6  2610.4   519.8 2633.61   542.9 2651.03
#Mann= 5 ,-1,0
       0      .1       0  350.27    .045       0  394.65      .1       0
     430     .06       0     530      .1       0
Bank Sta=350.27,394.65
XS Rating Curve= 0 ,0
Exp/Cntr=0.3,0.1

Type RM Length L Ch R = 1 ,4861    ,388.3,404.4,414.8
XS GIS Cut Line= 2
2197523.18895761574903.2516832482197503.89625935575421.328077426
#Sta/Elev= 30
       0 2632.23      58 2617.13      74 2606.51      90 2601.41     106 2593.79
     126 2579.74     146 2576.64     166  2560.9     174 2557.94   206.1 2555.57
   231.7 2559.15   266.1 2559.88   278.1 2563.15   298.1 2560.44   326.2 2561.39
   330.2 2560.36  335.342556.502   340.5 2554.88   358.2 2554.59  370.212556.536
   382.2 2564.51     410 2566.11   421.5 2571.93   434.2 2581.84   446.2 2595.46
   456.3 2604.78   466.3 2620.21   478.3 2631.44   502.3 2658.93   518.4 2670.62
#Mann= 5 ,-1,0
       0      .1       0     310     .06       0  335.34    .045       0
  370.21     .06       0     410      .1       0
Bank Sta=335.34,370.21
XS Rating Curve= 0 ,0
Exp/Cntr=0.3,0.1

Type RM Length L Ch R = 1 ,4457    ,351.4,345.6,341.1
XS GIS Cut Line= 4
2197239.37353371 574839.232074772197211.89632911575040.454571093
2197050.92512339575246.7615413192197035.35418693575345.853708274
#Sta/Elev= 30
       0 2621.16    22.3  2620.2    62.5 2616.31    82.7 2605.13    90.8  2602.3
   102.9 2600.12   132.4 2585.27   171.5 2574.64   199.8 2562.72   209.1 2557.02
   214.2 2555.34   280.4 2551.87   295.3 2549.53   305.5 2550.06   330.8 2549.22
  352.932550.075   371.6 2552.14   380.1 2556.34   384.7 2557.39   397.2 2554.21
   432.3 2554.33   451.3 2557.49   457.7 2559.52   462.8 2562.66   475.3 2574.19
   487.5  2583.3   507.7 2602.47   519.9 2610.34   544.1  2628.8   565.1 2646.59
#Mann= 5 ,-1,0
       0      .1       0   305.5    .045       0  352.93      .1       0
  393.09     .06       0  534.77      .1       0
Bank Sta=305.5,352.93
XS Rating Curve= 0 ,0
Exp/Cntr=0.3,0.1

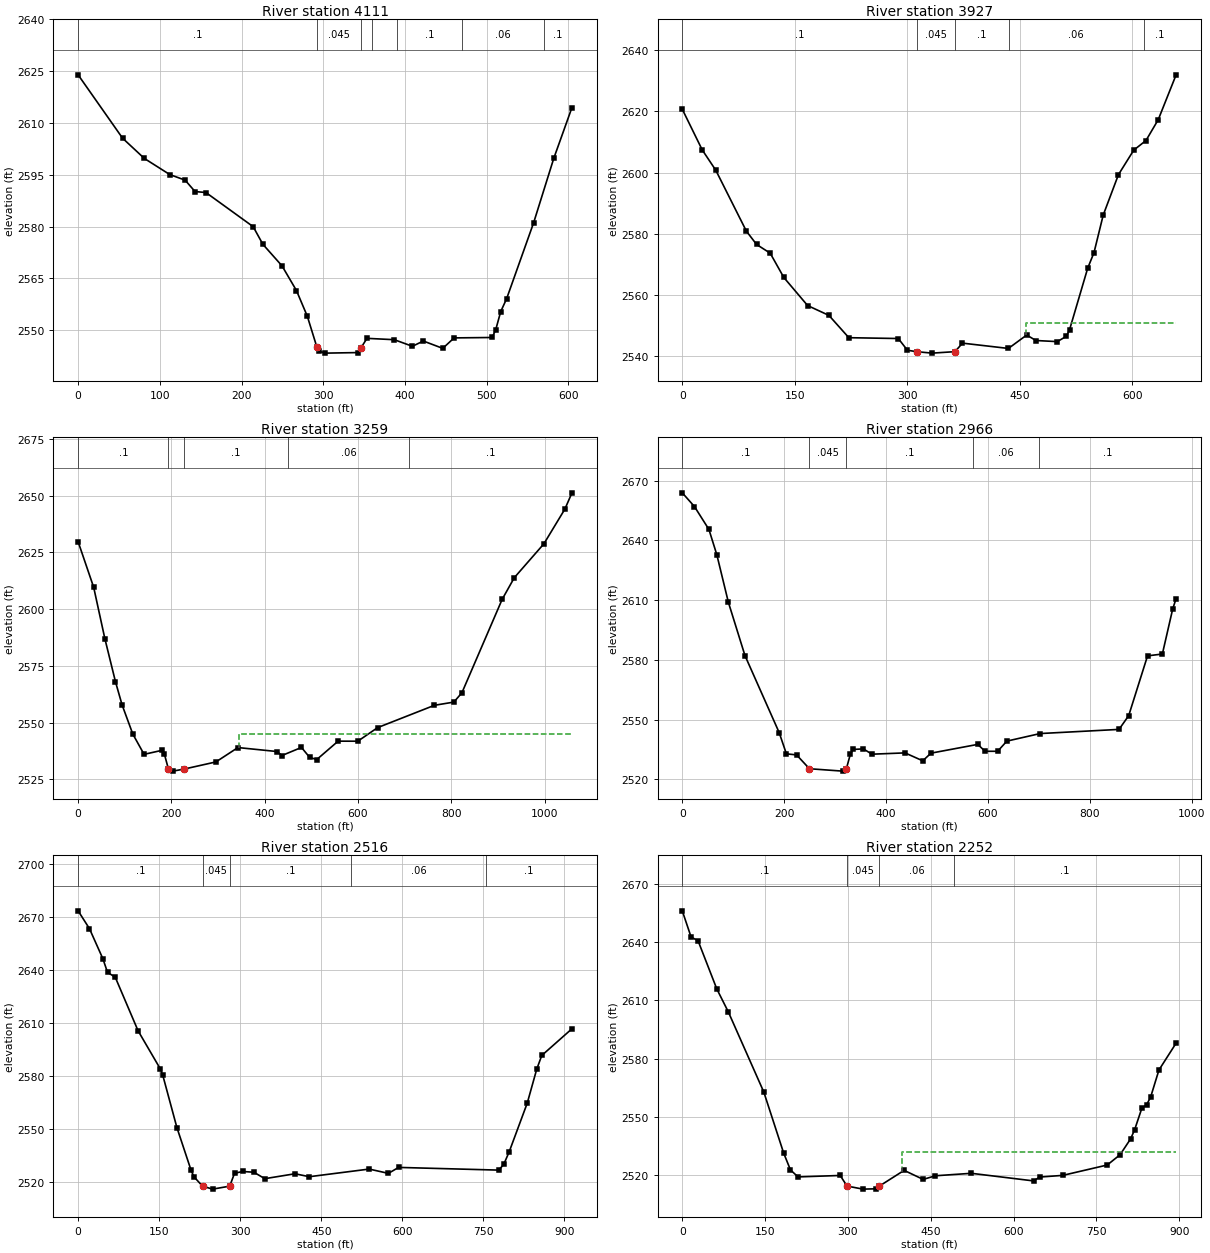
Type RM Length L Ch R = 1 ,4111    ,188,184.7,174.7
XS GIS Cut Line= 2
2196964.65152492574696.0789979072196703.99512104575241.254715885
#Sta/Elev= 30
       0 2623.97    54.4 2605.62      81 2599.76   112.2 2595.08   130.9 2593.47
   143.1 2590.16   156.4 2589.88   214.2 2579.99   226.1 2574.88   249.5 2568.64
   267.2 2561.48   280.5 2554.03  292.312544.998   295.1 2543.87   302.7 2543.36
   342.6 2543.52  346.362544.986   353.5 2547.64   386.9 2547.25   409.1 2545.34
   422.4 2546.87   446.2 2544.74   460.1 2547.77   506.7 2547.89   511.1  2550.2
   517.1 2555.37   524.4 2559.15   557.5 2581.19     582 2599.74   604.3  2614.5
#Mann= 7 ,-1,0
       0      .1       0  292.31    .045       0  346.36      .1       0
     360     .06       0     390      .1       0     470     .06       0
     570      .1       0
Bank Sta=292.31,346.36
XS Rating Curve= 0 ,0
Exp/Cntr(USF)=0,0
Exp/Cntr=0.3,0.1

Type RM Length L Ch R = 1 ,3927    ,656.7,667.6,683.6
XS GIS Cut Line= 3
2196797.06459912574621.6747559672196667.78199224574864.729148659
2196593.58027348575240.525978886
#Sta/Elev= 30
       0 2620.72    26.6 2607.43    44.7 2600.78    85.5 2580.88    99.1 2576.54
   117.2  2573.7   135.4 2565.76   167.1 2556.59   195.5 2553.38   222.1 2546.09
     288 2545.82   300.2 2541.99   312.8 2541.51   333.2 2541.05  363.58 2541.53
   373.6 2544.31   434.8 2542.58   459.2 2546.96   471.5 2545.17     500 2544.81
   512.2 2546.57   516.3 2548.66   540.5 2568.78   548.9 2573.86   561.2 2586.13
   581.5 2599.34   601.9 2607.35   618.2 2610.49   634.6 2617.32   658.4 2631.95
#Mann= 5 ,-1,0
       0      .1       0   312.8    .045       0  363.58      .1       0
   435.3     .06       0   615.3      .1       0
#XS Ineff= 2 , 0
                          458.78         2550.94
Permanent Ineff=
       F       F
Bank Sta=312.8,363.58
XS Rating Curve= 0 ,0
Exp/Cntr=0.3,0.1

Type RM Length L Ch R = 1 ,3259    ,287.8,292.6,293.4
XS GIS Cut Line= 3
2196479.51771003574379.7094398422195985.97215813574962.749321893
2196097.61756487575235.500309839
#Sta/Elev= 30
       0  2629.7    33.4  2609.6    57.3 2587.05      80 2568.11    94.2 2557.88
   117.2 2545.02   141.4 2536.07   179.4 2537.82   185.1 2536.06   193.6  2529.6
   203.3 2528.68   227.3 2529.59   295.4 2532.73   342.6 2539.06   426.2 2537.31
   436.9 2535.55   478.8 2539.11   496.1 2534.79   511.4 2533.75   557.4 2541.88
   599.5 2541.85     642 2547.83   763.9 2557.67   805.4 2559.07   822.7 2563.17
   909.1 2604.36   935.1 2613.87   998.5 2628.78  1043.5 2644.07  1058.6 2651.21
#Mann= 5 ,-1,0
       0      .1       0   193.6    .045       0   227.3      .1       0
     450     .06       0     710      .1       0
#XS Ineff= 2 , 0
                          343.96         2544.98
Permanent Ineff=
       F       F
Bank Sta=193.6,227.3
XS Rating Curve= 0 ,0
Exp/Cntr=0.3,0.1

Type RM Length L Ch R = 1 ,2966    ,451.1,450.4,449.7
XS GIS Cut Line= 2
2196268.63173657574174.4494556222195666.55215577574934.391365529
#Sta/Elev= 30
       0 2663.82    23.9 2656.94    52.3 2645.45    67.8 2632.78    90.5 2608.91
   123.1 2582.14   190.2 2543.51   204.4 2532.83   224.4 2532.29  249.642525.348
   314.8 2524.15  322.182525.347   330.1 2532.76   335.4 2535.05   355.6  2535.3
   372.4 2532.65   437.3  2533.3   472.1 2529.33   488.3 2533.17   580.1 2537.57
   594.5 2534.11   619.1 2534.11   637.2 2539.21   702.6 2543.01   857.4 2545.09
   876.4 2551.99   913.4    2582   942.5 2582.92   962.9 2605.65   969.5 2610.72
#Mann= 5 ,-1,0
       0      .1       0  249.64    .045       0  322.18      .1       0
     570     .06       0     700      .1       0
Bank Sta=249.64,322.18
XS Rating Curve= 0 ,0
Exp/Cntr(USF)=0,0
Exp/Cntr=0.3,0.1

Type RM Length L Ch R = 1 ,2516    ,260.4,264.4,266.4
XS GIS Cut Line= 3
2195920.79695526573969.4567406542195758.64624699574094.404421553
2195321.15526701574652.554703269
#Sta/Elev= 30
       0 2673.57      21 2663.49    45.9 2646.44    54.4 2638.79    68.7 2636.06
     111 2605.73   152.3 2584.11   156.8 2580.48   182.8 2551.05   208.7  2527.2
   214.1 2523.29  230.26  2517.9   248.9 2516.22  280.572517.899   289.5 2525.21
   304.8 2526.19   325.3 2525.77   345.5 2522.13   401.4 2524.91   427.8 2523.24
   538.6 2527.56   574.2 2525.13   593.1  2528.5   778.3 2526.97   787.6 2530.17
   797.8 2537.36   831.2 2564.88   848.6 2583.91     858 2591.78   913.9 2606.89
#Mann= 5 ,-1,0
       0      .1       0  230.26    .045       0  280.57      .1       0
  504.71     .06       0  754.71      .1       0
Bank Sta=230.26,280.57
XS Rating Curve= 0 ,0
Exp/Cntr=0.3,0.1

Type RM Length L Ch R = 1 ,2252    ,121.2,113.1,98.8
XS GIS Cut Line= 4
 2195803.3094211573793.2189090762195639.94026656573848.287163417
2195219.58592509574281.4907642342195111.28502488574329.216584663
#Sta/Elev= 30
       0 2655.98      16  2642.5    28.6  2640.6    62.5 2615.86    83.5 2603.98
   147.7 2562.83   183.6 2531.51   195.9 2522.85   209.6 2519.23     286 2519.97
   298.4 2514.53   327.2 2512.95   351.1 2513.12  357.152514.545   401.8 2522.59
   436.3 2517.95   458.6 2519.82   523.6 2521.08   636.3 2517.17   647.4 2519.16
     689 2520.01   769.7 2525.35   792.9 2530.63   811.8 2538.69   819.1 2543.33
   832.2 2554.42   840.9 2556.32   848.2 2560.22   863.3 2574.17   894.4 2587.99
#Mann= 4 ,-1,0
       0      .1       0   298.4    .045       0  357.15     .06       0
   492.4      .1       0
#XS Ineff= 2 , 0
                          398.53         2531.96
Permanent Ineff=
       F       F
Bank Sta=298.4,357.15
XS Rating Curve= 0 ,0
Exp/Cntr(USF)=0,0
Exp/Cntr=0.3,0.1