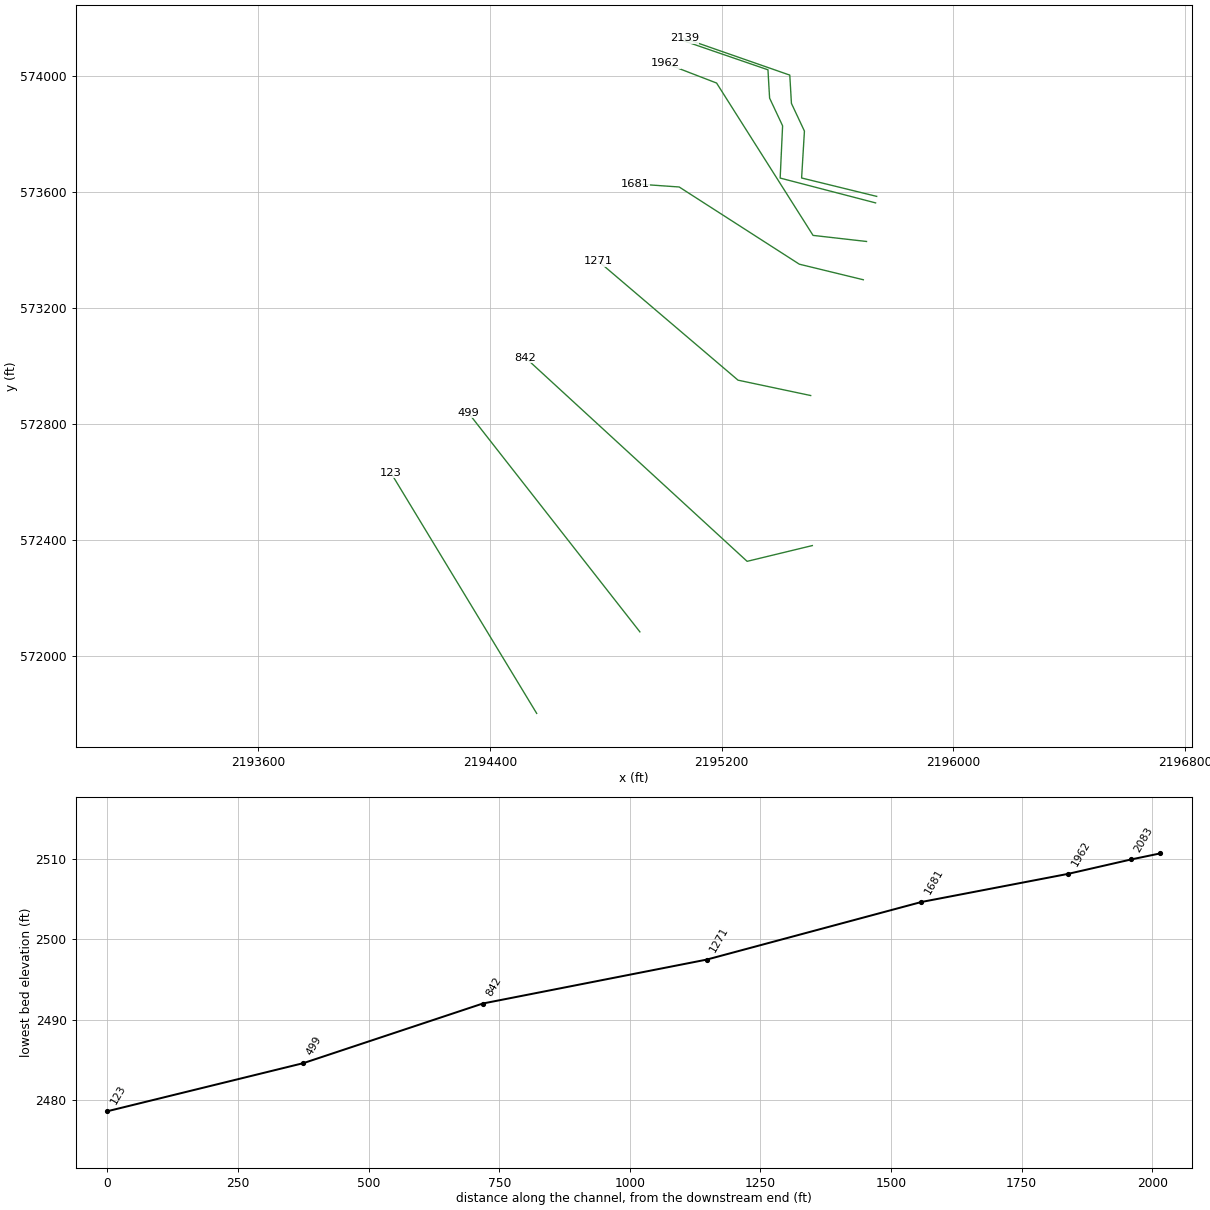
HEC-RAS study BFKELKRV.prj: BFKELKRV

--- BFKELKRV.g01 (geometry) --- (continued)

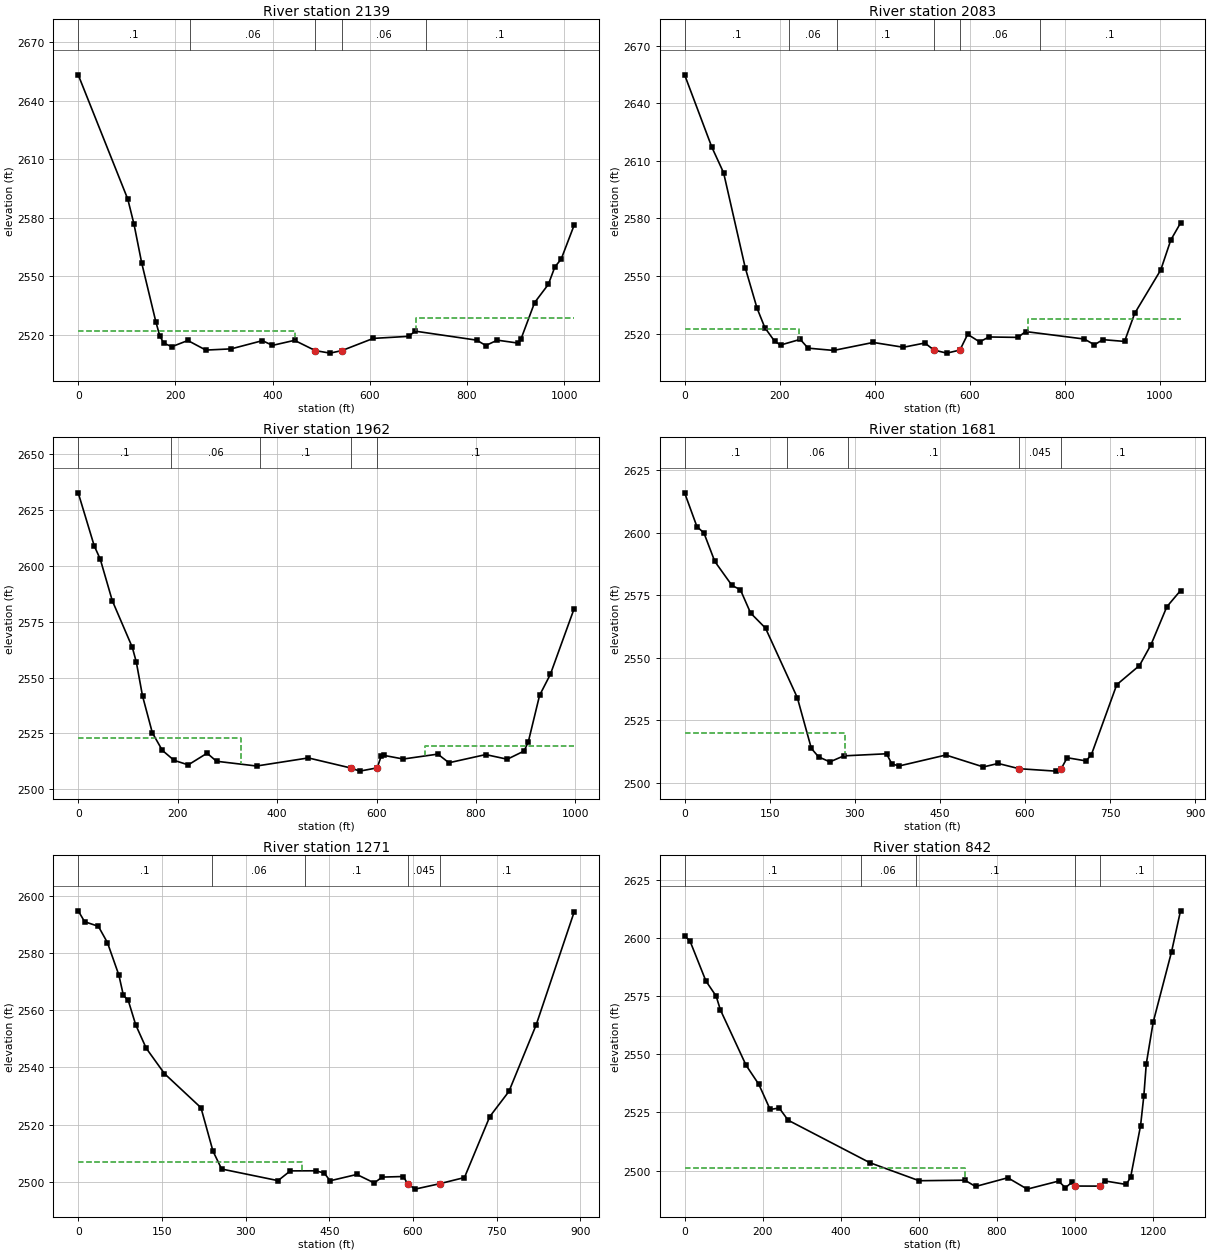
Type RM Length L Ch R = 1 ,2139    ,58.2,55.6,65.3
XS GIS Cut Line= 6
2195735.29810622573585.846202359 2195476.1215585573649.345358232
2195485.87044205573811.2307818112195440.99663221573906.831507118
2195435.31377476574004.5428454292195070.96659316574131.514891119
#Sta/Elev= 30
       0 2653.23   102.1 2589.49   114.9 2576.62   130.6 2556.93   159.7 2526.79
   167.9 2519.45   176.2 2515.75   192.7 2513.96   225.6 2517.13   262.7 2512.22
   314.8 2512.84   379.1 2517.05   399.8 2514.63   445.2 2517.21     488 2511.95
   518.3 2510.66   542.6 2511.95   607.3 2518.21   680.5 2519.26   693.2 2521.93
   820.3  2517.3   838.8 2514.56   862.6  2517.3   904.8 2515.82     911 2517.69
   939.3 2536.54   967.6 2545.89   981.2 2554.93   993.9 2558.74  1020.6 2576.15
#Mann= 5 ,-1,0
       0      .1       0     230     .06       0     488    .045       0
   542.6     .06       0   714.8      .1       0
#XS Ineff= 2 , 0
          447.03 2521.91  695.31         2528.54
Permanent Ineff=
       F       F
Bank Sta=488,542.6
XS Rating Curve= 0 ,0
Exp/Cntr=0.3,0.1

Type RM Length L Ch R = 1 ,2083    ,115.2,120.5,119.6
XS GIS Cut Line= 6
2195731.55294034573563.3546505342195402.09580459573649.071540688
2195410.48441869573829.5473133592195365.61060885573925.148038666
 2195359.9277514574022.8593769772195060.88690338574125.604879564
#Sta/Elev= 30
       0 2654.78    57.2 2617.16      82  2603.8   127.5 2554.38   152.3 2533.35
   168.8 2523.15   189.5 2516.05   201.9 2514.13   243.2 2517.07   259.7  2512.5
   313.5 2511.31   396.7 2515.47   460.2 2512.96   505.5 2515.18   524.3 2511.52
   551.5 2509.91  579.162511.503   595.4 2519.71   620.6 2515.75     640 2518.32
   701.2  2518.1   717.3 2521.14     841 2517.24   862.1 2514.24   879.8 2516.93
   925.5    2516   946.7 2530.56  1001.7 2553.24  1022.8 2568.81  1043.2 2577.62
#Mann= 6 ,-1,0
       0      .1       0     220     .06       0     320      .1       0
   524.3    .045       0  579.16     .06       0  747.02      .1       0
#XS Ineff= 2 , 0
          240.81 2522.71  721.76         2527.54
Permanent Ineff=
       F       F
Bank Sta=524.3,579.16
XS Rating Curve= 0 ,0
Exp/Cntr=0.3,0.1

Type RM Length L Ch R = 1 ,1962    ,266.4,281,291.6
XS GIS Cut Line= 4
2195700.20925547573430.1465579792195515.65680334573451.120531754
2195182.56766467573977.1578844352195006.34925077574045.075398122
#Sta/Elev= 30
       0 2632.75    32.2 2609.01    44.3 2603.06    68.5 2584.46   108.7 2563.61
   116.8    2557   129.3 2541.81     149 2525.34   169.1 2517.43   192.9 2512.93
   221.3 2510.92   259.2 2516.15   278.1 2512.54   358.6 2510.41   462.8 2514.03
     548 2509.53   566.1 2508.12  601.142509.582   609.5 2514.95   614.3 2515.19
   653.6 2513.54   723.2 2515.74   745.5 2511.87   819.5 2515.53   862.8 2513.45
   896.7 2517.13   905.2  2521.3   927.8 2542.06   949.5 2551.48   997.2 2580.83
#Mann= 5 ,-1,0
       0      .1       0  185.74     .06       0  365.74      .1       0
     548    .045       0  601.14      .1       0
#XS Ineff= 2 , 0
          326.51 2522.91  696.69         2519.37
Permanent Ineff=
       F       F
Bank Sta=548,601.14
XS Rating Curve= 0 ,0
Exp/Cntr(USF)=0,0
Exp/Cntr=0.3,0.1

Type RM Length L Ch R = 1 ,1681    ,412.6,410.9,408.6
XS GIS Cut Line= 4
2195689.21629173573297.9524489282195468.31327671 573351.68591287
2195053.45892411573618.2600867762194900.14678304573629.008960266
#Sta/Elev= 30
       0 2615.92    21.7  2602.4      34 2599.89    53.2 2588.48    83.4  2578.9
    98.3 2577.16   116.3 2567.85   142.6 2561.81   198.7 2533.99   223.4  2513.7
   236.1 2510.34     256 2508.31   280.6 2510.72   355.9 2511.56   365.4  2507.5
   378.1 2506.68   460.5 2511.06   526.7 2506.29   552.7 2507.69  589.552505.593
     654 2504.62  663.882505.593   674.4 2509.98   707.7  2508.7   717.2 2511.26
   761.8 2539.19   801.9 2546.86   822.2  2555.2   850.1 2570.36   874.2 2576.82
#Mann= 5 ,-1,0
       0      .1       0     180     .06       0  287.34      .1       0
  589.55    .045       0  663.88      .1       0
#XS Ineff= 2 , 0
        283.5551    2520
Permanent Ineff=
       F       F
Bank Sta=589.55,663.88
XS Rating Curve= 0 ,0
Exp/Cntr=0.3,0.1

Type RM Length L Ch R = 1 ,1271    ,429.1,428.6,427.2
XS GIS Cut Line= 3
2195507.46608767572898.2235026532195256.59959568572951.252192019
2194775.26226144573361.204752113
#Sta/Elev= 30
       0 2594.79    11.5 2590.98    36.1 2589.38    52.4 2583.66    72.9 2572.29
      81  2565.2    89.6  2563.5   103.1 2554.89   121.9 2546.73   154.6 2537.85
     220 2525.93   241.5 2510.75     257 2504.49   358.1 2500.43   380.1 2503.84
   425.5 2503.87   440.9 2503.09   451.4 2500.38   499.3 2502.59   530.5 2499.63
   544.7 2501.67   582.7 2501.87  590.322499.344   603.7 2497.46  647.552499.344
   692.2 2501.51   737.6 2522.83   771.9 2531.63   820.8 2554.94   888.7 2594.33
#Mann= 5 ,-1,0
       0      .1       0     240     .06       0  406.41      .1       0
  590.32    .045       0  647.55      .1       0
#XS Ineff= 2 , 0
        400.7803    2507
Permanent Ineff=
       F       F
Bank Sta=590.32,647.55
XS Rating Curve= 0 ,0
Exp/Cntr(USF)=0,0
Exp/Cntr=0.3,0.1

Type RM Length L Ch R = 1 ,842     ,343.8,343.4,325.2
XS GIS Cut Line= 3
2195513.17686961572380.173998851 2195288.0088963572325.717614003
2194522.96807395573028.551704594
#Sta/Elev= 30
       0 2600.68    13.4 2598.78    54.5 2581.46    80.8 2574.93    91.6 2569.05
   157.4 2545.25   190.3 2536.98   219.1 2526.23   242.3 2526.86   265.1 2521.63
   474.6 2503.35   600.8 2495.61   718.1 2495.84   745.3 2493.13     828 2496.88
   877.8    2492   958.1 2495.45   975.6 2492.59   993.6 2495.14   999.5 2493.33
  1063.5 2493.29  1076.4 2495.53  1131.4 2494.01  1142.7 2497.12  1168.2 2519.33
  1176.6  2532.2  1182.8 2545.83  1200.5 2563.74  1247.5 2593.97  1270.5  2611.6
#Mann= 5 ,-1,0
       0      .1       0  451.66     .06       0  591.66      .1       0
   999.5    .045       0  1063.5      .1       0
#XS Ineff= 2 , 0
          718.38 2501.04
Permanent Ineff=
       F       F
Bank Sta=999.5,1063.5
XS Rating Curve= 0 ,0
Exp/Cntr(USF)=0,0
Exp/Cntr=0.3,0.1

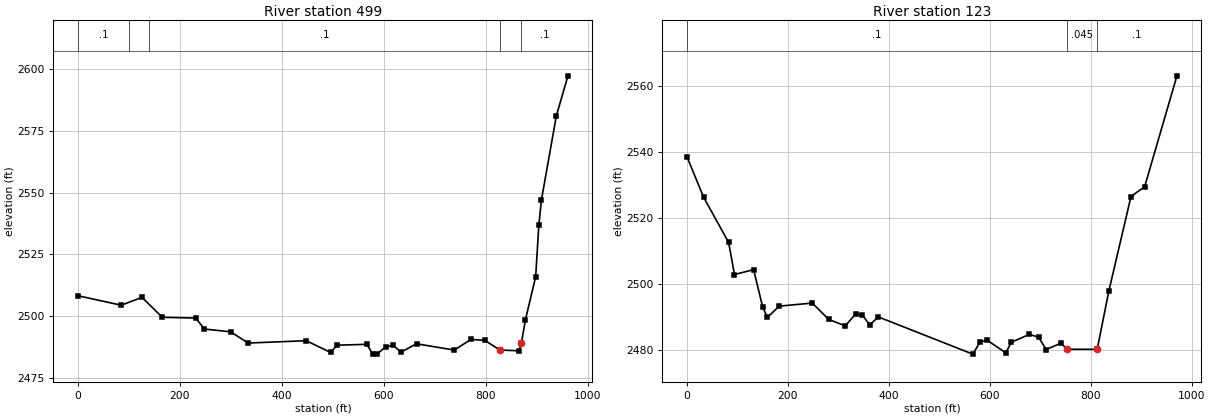
Type RM Length L Ch R = 1 ,499     ,379.1,375.2,368
XS GIS Cut Line= 2
2194917.72176171572082.2378325552194325.00108209572839.021009015
#Sta/Elev= 30
       0 2508.25      85 2504.41   125.7 2507.59   165.6 2499.51   231.1 2499.19
   248.2 2494.75   299.5 2493.63     334 2489.08   447.7 2490.03   495.5 2485.31
   508.5 2488.21   566.9 2488.56   577.9 2484.75   586.4 2484.59   604.4 2487.64
   618.6 2488.11   633.8 2485.41   664.2 2488.78   738.3 2486.23   770.9 2490.54
   798.1 2490.18   827.62486.267   865.3 2485.93     8702489.162   877.9 2498.55
   897.9 2515.91   904.2 2536.99   909.3 2547.12   938.6 2581.24   961.3 2597.33
#Mann= 5 ,-1,0
       0      .1       0     100     .06       0     140      .1       0
   827.6    .045       0     870      .1       0
Bank Sta=827.6,870
XS Rating Curve= 0 ,0
Exp/Cntr(USF)=0,0
Exp/Cntr=0.3,0.1

Type RM Length L Ch R = 1 ,123     ,,,
XS GIS Cut Line= 2
2194561.35845642571800.7873192172194058.13144082  572631.1197656
#Sta/Elev= 30
       0  2538.5    33.2 2526.15    82.7 2512.47    94.3 2502.75   132.2 2504.22
   150.1 2492.89   159.5 2489.74   182.9 2493.16   248.4 2494.09   281.1 2489.11
   313.8 2487.19   334.1 2490.74   347.7 2490.42   362.3 2487.49   379.3 2489.89
   566.4 2478.61   580.7 2482.24   594.5 2482.85   631.9 2478.99   642.8 2482.23
   678.7 2484.59   696.9 2483.74   711.7 2480.01   740.9 2481.92   753.5 2480.08
  812.872480.066   835.8 2497.62   879.8 2526.38   906.9 2529.38   970.9 2562.98
#Mann= 3 ,-1,0
       0      .1       0   753.5    .045       0  812.87      .1       0
Bank Sta=753.5,812.87
XS Rating Curve= 0 ,0
Exp/Cntr(USF)=0,0
Exp/Cntr=0.3,0.1
LCMann Table=0

Chan Stop Cuts=-1
Use User Specified Reach Order=0
Composite Channel Slope=5